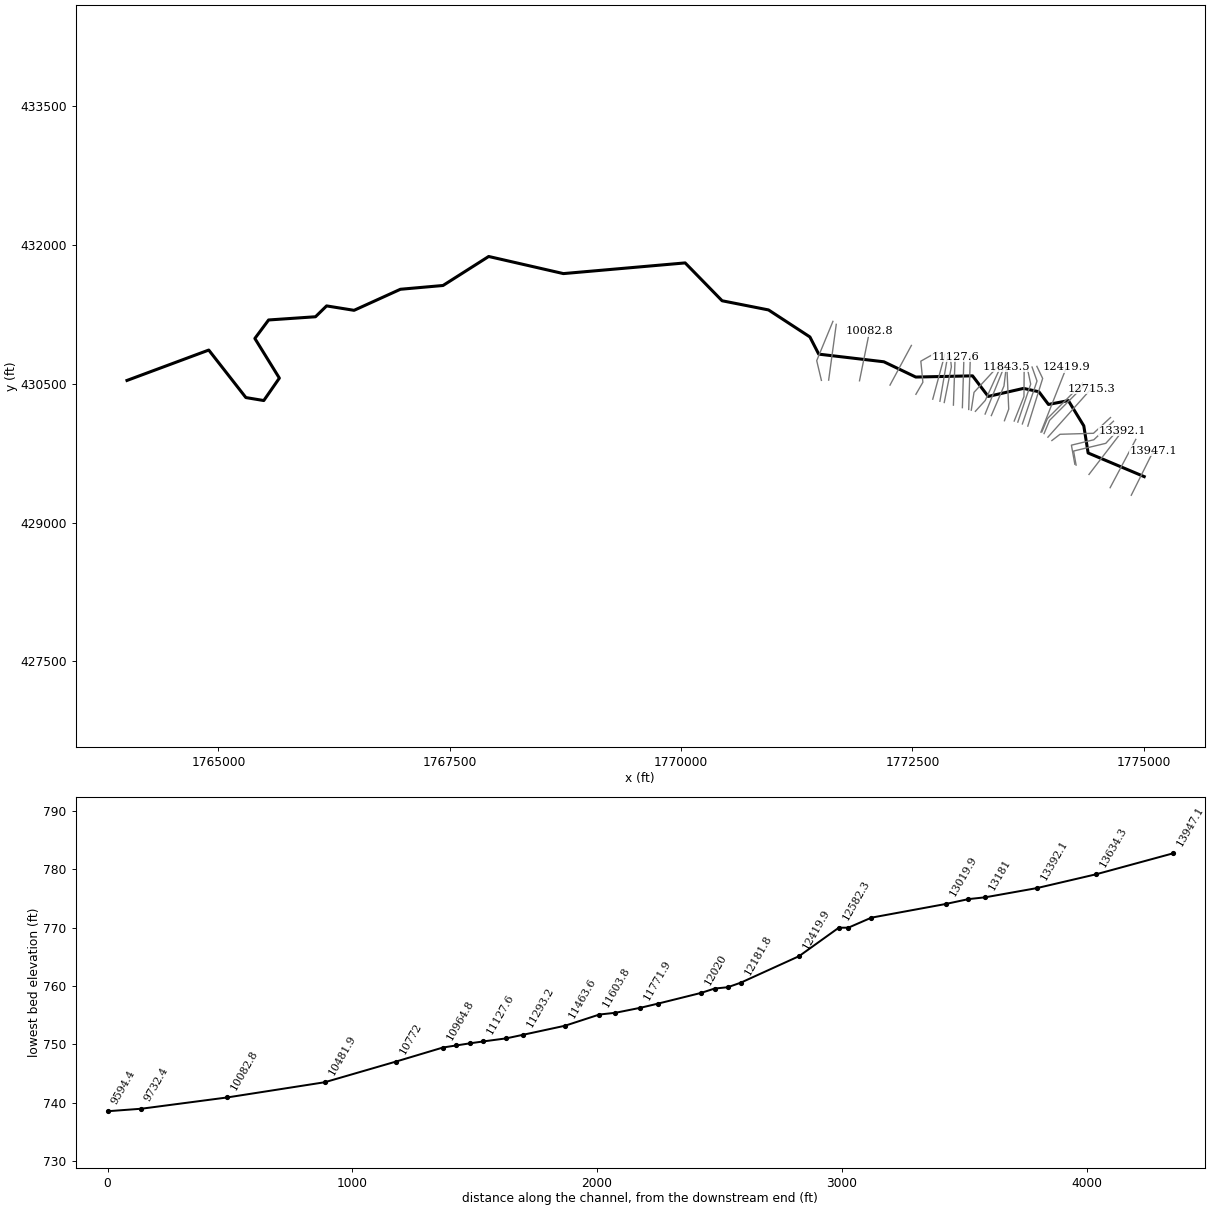
--- LICKCK.prj (project) ---

Proj Title=LICKCK
Current Plan=p01
Default Exp/Contr=0,0
English Units
Geom File=g01
Flow File=f01
Plan File=p01
BEGIN DESCRIPTION:
END DESCRIPTION:
DSS Export Rating Curves= 0
DSS Export Rating Curve Sorted= 0
DSS Export Volume Flow Curves= 0
DXF OffsetX= 0
DXF OffsetY= 0
DXF ScaleX= 0
DXF ScaleY= 0

--- LICKCK.p01 (plan) ---

Plan Title=Floodplain
Program Version=4.00
Geom File=g01
Flow File=f01
K Sum by GR=0
Std Step Tol=0.01
Critical Tol=0.01
Num of Std Step Trials=20
Max Error Tol=0.3
Flow Tol Ratio=0.001
Split Flow NTrial=30
Split Flow Tol=0.02
Split Flow Ratio=0.02
Log Output Level=0
Friction Slope Method=1
Unsteady Friction Slope Method=2
Unsteady Bridges Friction Slope Method=1
Global Log Level=0
CheckData=False
Run HTab=0
Run UNet=0
Run PostProcess=0
UNET Theta=0
UNET Theta Warmup=0
UNET ZTol=0
UNET ZSATol=0
UNET MxIter=0
UNET MaxInSteps=0
UNET DtIC=0
UNET DtMin=0
UNET MaxCRTS=0
UNET WFStab=0
UNET SFStab=0
UNET WFX=0
UNET SFX=0
UNET DSS MLevel=0
UNET DZMax Abort=0
UNET Convert EG Bridges=0
UNET Use Existing IB Tables=0
UNET Froude Limit=0
UNET Froude Power=0
Write IC File=0
Echo Input=False
Echo Output=False
Write Detailed=0

--- LICKCK.f01 (steady flow) ---

Flow Title=NFF Regression Equation
Program Version=5.03
Number of Profiles= 1
Profile Names=P100yr
River Rch & RM=LICKCK,Main            ,13947.1
934.5631
River Rch & RM=LICKCK,Main            ,12715.3
1002.476
River Rch & RM=LICKCK,Main            ,12181.8
1333.154
River Rch & RM=LICKCK,Main            ,11293.2
1350.669
River Rch & RM=LICKCK,Main            ,8852.2
1488.828
River Rch & RM=LICKCK,Main            ,6718.5
 1592.48
River Rch & RM=LICKCK,Main            ,548.5
1760.975
River Rch & RM=LICKCK,Main            ,252.9
1763.907
Boundary for River Rch & Prof#=LICKCK,Main            , 1
Up Type= 0
Dn Type= 3
Dn Slope=0.00402
DSS Import GetInterval= 0
DSS Import GetPeak= 0
DSS Import FillOption= 0

--- LICKCK.g01 (geometry) ---

Geom Title=USGS 10m DEM
Program Version=5.03

River Reach=LICKCK          ,Main
Reach XY= 30
     1775004.733      429495.632     1774398.572      429750.887
     1774351.781      430043.942     1774185.114      430316.512
     1773969.889      430274.973     1773866.538      430411.998
     1773700.739      430448.456     1773318.794      430361.651
     1773149.524      430583.873     1772535.809      430570.852
      1772191.19      430735.783     1771487.197      430818.248
     1771391.711      431004.012     1770944.663      431295.678
     1770442.927      431394.637     1770043.621      431803.491
     1768727.649       431688.04     1767920.357      431872.935
     1767426.878      431559.648     1766966.364      431518.769
     1766465.496      431291.425     1766168.621      431339.168
      1766048.83       431221.98     1765541.885      431187.258
     1765393.448      430987.606     1765658.204      430559.394
     1765489.802      430317.206     1765296.225      430349.324
     1764895.184      430862.345     1764011.503       430534.22

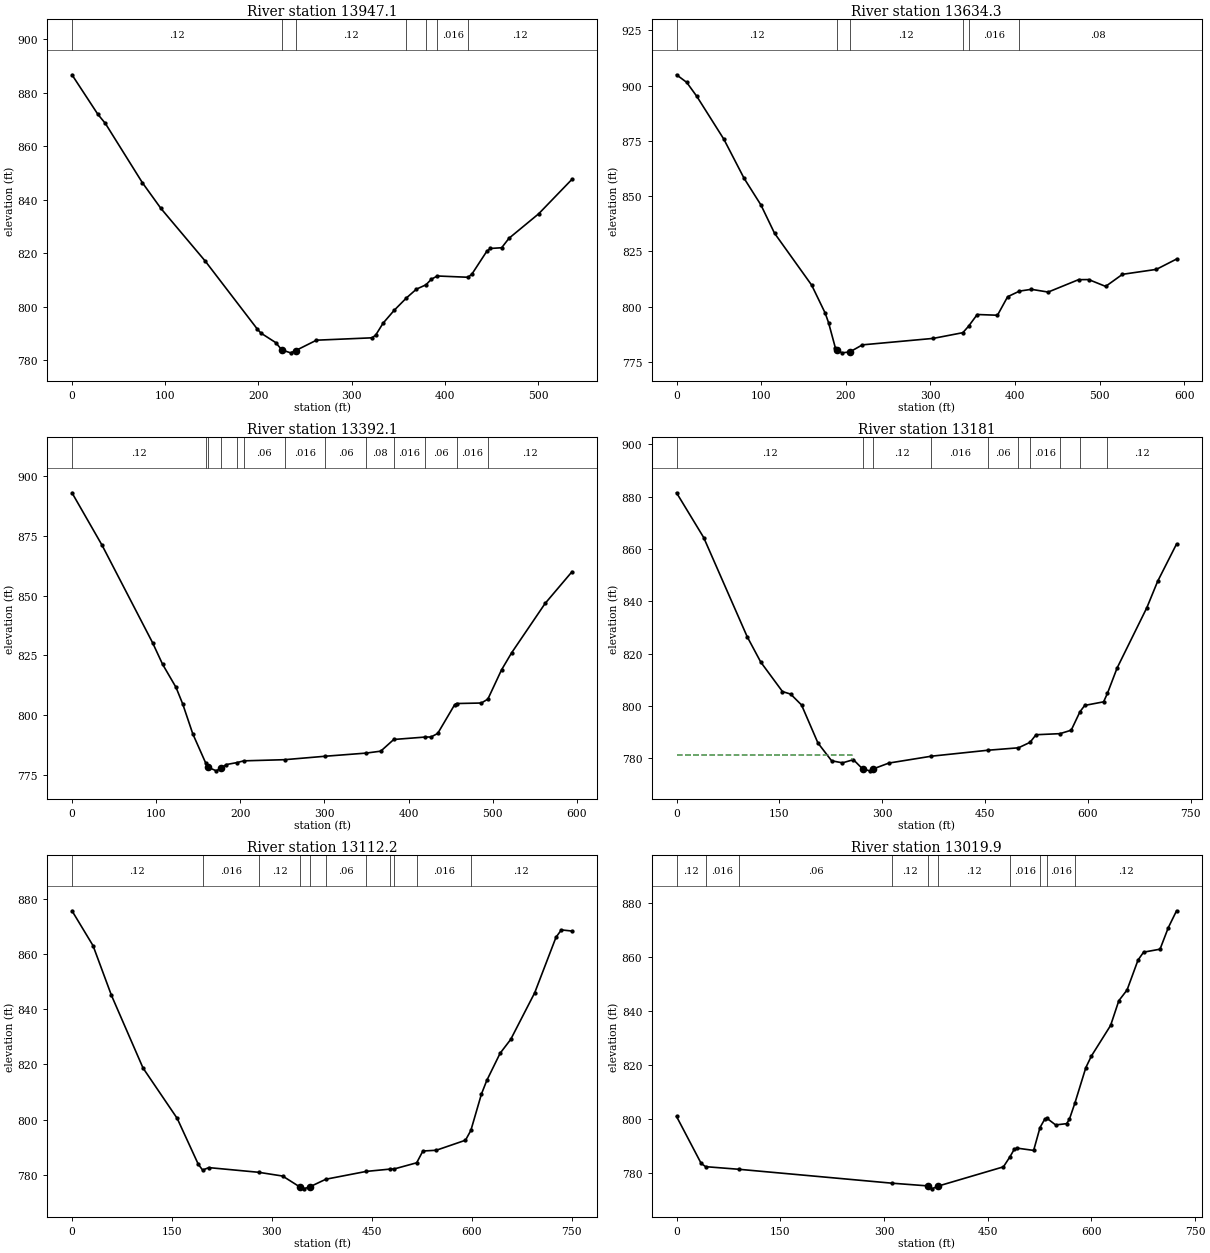
Type RM Length L Ch R = 1 ,13947.1 ,313.3,312.8,311.2
XS GIS Cut Line= 2
     1774864.736       429294.62     1775104.652      429774.453
#Sta/Elev= 30
       0  886.71    27.8  871.91    35.8  868.52    75.5  846.36    95.4  836.73
   143.1  816.97   198.7  791.66   202.7   790.1   218.6  786.54   225.1  783.82
   234.5  782.71   240.1  783.57   262.3  787.44   321.9  788.33   325.9  789.37
   333.8  793.81   345.7  798.62  358.89803.2651   369.6  806.54  379.82 808.161
   385.5  810.22  391.91811.4557  424.93810.9774   429.2  812.22   445.1  820.72
     449  821.75     461  822.02   468.9  825.57   500.7  834.71   536.5  847.63
#Mann= 7 ,-1 , 0
       0     .12       0   225.1    .045       0   240.1     .12       0
  358.89     .08       0  379.82     .12       0  391.91    .016       0
  424.93     .12       0
Bank Sta=225.1,240.1
XS Rating Curve= 0 ,0
Exp/Cntr=0.3,0.1

Type RM Length L Ch R = 1 ,13634.3 ,245.9,242.2,239.2
XS GIS Cut Line= 2
     1774636.451       429375.94     1774913.631      429897.692
#Sta/Elev= 30
       0  904.92      12   901.5      24  895.14    55.9  875.79    79.8  858.11
    99.8  845.98   115.8  833.24   159.7  809.75   175.6  797.15   179.6  792.83
   187.6  781.48   189.8  780.29   195.6  779.14   204.8  779.56   219.6  782.75
   303.4  785.68  338.29 788.261     345791.1602   355.3  796.48   379.2  796.15
   391.2  804.52  405.18807.0594   419.2  807.87   439.1  806.63     475  812.24
     487  812.28     507  809.19   526.9  814.66   566.9  816.89   590.8  821.57
#Mann= 6 ,-1 , 0
       0     .12       0   189.8    .045       0   204.8     .12       0
  338.29     .08       0     345    .016       0  405.18     .08       0
Bank Sta=189.8,204.8
XS Rating Curve= 0 ,0
Exp/Cntr=0.3,0.1

Type RM Length L Ch R = 1 ,13392.1 ,226.6,211.1,195.5
XS GIS Cut Line= 2
     1774407.933      429519.303     1774770.252      429990.194
#Sta/Elev= 30
       0  892.96    35.9  870.94    95.7  830.36   107.7  821.27   123.6  811.66
   131.6   804.7   143.6  792.18  158.79780.1259  161.92778.2384   171.5  776.77
  176.99777.9327   183.4   779.4  196.06780.2143  204.25780.9461  252.68781.4304
  301.12782.8752  349.55784.1864   366.9  784.99  382.39789.8762  419.66790.8868
   426.7  790.92   434.6   792.4   454.6  804.33  456.93 804.895   486.5  805.11
   494.2 806.744   510.4  818.94   522.4  826.08   562.2  846.71   594.2  859.98
#Mann= 13 ,-1 , 0
       0     .12       0  158.79     .06       0  161.92    .045       0
  176.99     .06       0  196.06     .12       0  204.25     .06       0
  252.68    .016       0  301.12     .06       0  349.55     .08       0
  382.39    .016       0  419.66     .06       0  456.93    .016       0
   494.2     .12       0
Bank Sta=161.92,176.99
XS Rating Curve= 0 ,0
Exp/Cntr=0.3,0.1

Type RM Length L Ch R = 1 ,13181   ,68.7,68.8,69.1
XS GIS Cut Line= 4
     1774268.634      429619.712     1774241.426      429771.799
     1774589.516      429855.133      1774736.07      430014.727
#Sta/Elev= 30
       0  881.44    39.6  864.34     103  826.46   122.8  816.75   154.5  805.48
   166.4  804.51   182.3  800.35   206.2  785.83   226.1  779.04     242  778.24
   257.9  779.46   271.3  775.92   281.8  775.19   286.3  775.88   309.6  778.16
  371.71780.7889  453.79783.0573  498.57783.9921  515.45786.0807   524.2  788.99
  559.12789.3966   575.5  790.72  588.25797.7679   595.2  800.19   622.7  801.56
  628.35804.8327   642.4  814.48   685.8  837.55   701.5   847.6   729.1  861.88
#Mann= 10 ,-1 , 0
       0     .12       0   271.3    .045       0   286.3     .12       0
  371.71    .016       0  453.79     .06       0  498.57     .08       0
  515.45    .016       0  559.12     .06       0  588.25    .016       0
  628.35     .12       0
#XS Ineff= 2 , 0
          255.93  781.28
Permanent Ineff=
       F       F
Bank Sta=271.3,286.3
XS Rating Curve= 0 ,0
Exp/Cntr=0.3,0.1

Type RM Length L Ch R = 1 ,13112.2 ,96.9,92.3,87.4
XS GIS Cut Line= 4
     1774255.095      429629.471     1774217.815      429835.341
      1774460.31      429893.697     1774672.356      430094.044
#Sta/Elev= 30
       0  875.73    31.6  863.08    59.2  845.07   106.6  818.71   157.9  800.43
   189.5  783.81  196.04 781.684   205.3  782.58  280.01780.8847   316.1  779.52
   342.7  775.45   347.8  774.88   357.7   775.7  380.98778.3645  441.74781.2061
  476.67782.0255   483.8  782.11   517.3784.3315   526.6   788.6   546.6  788.87
   590.5  792.51  598.57796.0537   614.5  809.29   622.5   814.2   642.5  824.06
   658.4  829.08   694.4  845.99   726.4  866.15   734.4  868.79   750.4  868.38
#Mann= 11 ,-1 , 0
       0     .12       0  196.04    .016       0  280.01     .12       0
   342.7    .045       0   357.7     .12       0  380.98     .06       0
  441.74     .08       0  476.67    .016       0   483.8     .12       0
   517.3    .016       0  598.57     .12       0
Bank Sta=342.7,357.7
XS Rating Curve= 0 ,0
Exp/Cntr=0.3,0.1

Type RM Length L Ch R = 1 ,13019.9 ,285.7,304.6,323.4
XS GIS Cut Line= 4
     1774006.974      429885.372     1774094.882      429952.821
     1774456.703      429963.639     1774640.507      430133.694
#Sta/Elev= 30
       0   800.9    35.6   783.5   42.06782.2709   90.58781.2932  312.21776.1321
   363.5  775.14   369.4  774.05   378.5  775.08   472.8  782.21  482.22785.9326
   488.7  788.82   492.7  789.14   516.5   788.3  525.71 796.784   532.4  799.82
  535.79800.1929   548.3  797.75   564.2  798.22   568.2  799.86  576.03 805.749
     592  819.02     600  823.29   627.8  834.64   639.7  843.82   651.6  847.79
   667.5  858.91   675.5  861.81   699.3  862.92   711.3  870.94   723.2  877.16
#Mann= 10 ,-1 , 0
       0     .12       0   42.06    .016       0   90.58     .06       0
  312.21     .12       0   363.5    .045       0   378.5     .12       0
  482.22    .016       0  525.71     .12       0  535.79    .016       0
  576.03     .12       0
Bank Sta=363.5,378.5
XS Rating Curve= 0 ,0
Exp/Cntr=0.3,0.1

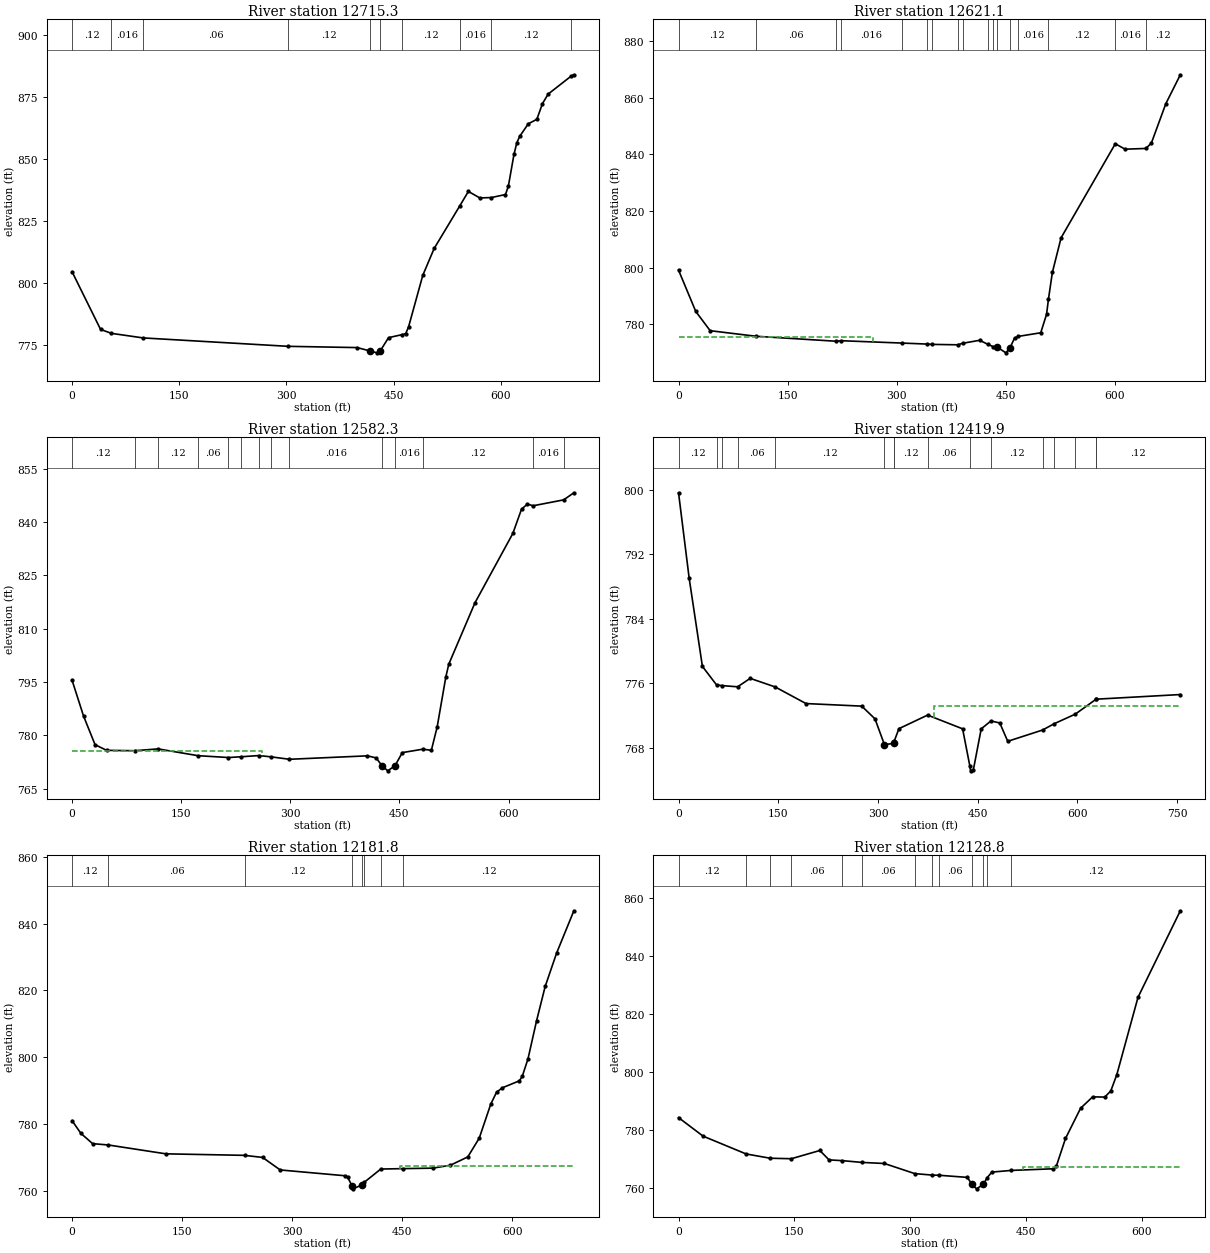
Type RM Length L Ch R = 1 ,12715.3 ,96.7,94.2,92.8
XS GIS Cut Line= 2
     1773964.102      429921.814      1774432.31      430445.177
#Sta/Elev= 30
       0  804.44    39.9  781.15   55.11779.5676    99.4 777.724   302.5774.3275
     399  773.82   416.4   772.5   426.9   771.7   431.4  772.55   442.9  777.84
  461.02778.9923   466.8  779.42   470.8  782.09   490.8     803   506.7  813.85
  542.39830.9619   554.6  836.87   570.6  834.25  586.69834.4043   606.5  835.62
   610.5  838.95   618.4  851.81   622.4  856.57   626.4  859.11   638.4  864.18
   650.4  865.99   658.3  872.36   666.3   876.2   698.8883.5295   702.2  883.98
#Mann= 10 ,-1 , 0
       0     .12       0   55.11    .016       0    99.4     .06       0
   302.5     .12       0   416.4    .045       0   431.4    .016       0
  461.02     .12       0  542.39    .016       0  586.69     .12       0
   698.8      .1       0
Bank Sta=416.4,431.4
XS Rating Curve= 0 ,0
Exp/Cntr=0.3,0.1

Type RM Length L Ch R = 1 ,12621.1 ,59.3,38.8,35.3
XS GIS Cut Line= 3
      1773922.46      429960.346     1773981.488      430102.707
     1774359.266      430482.568
#Sta/Elev= 30
       0  799.16    23.7  784.57    43.5  777.79  106.43775.8287  216.95 774.067
  223.45774.2605  307.22773.4256  341.92773.0706   349.1772.9605  383.58772.8153
  390.99773.3691     414  774.41  425.23772.9782  432.87772.1234     438  772.01
     450  769.98  455.68771.7709     462  775.24  466.89775.7778   497.9  777.06
   505.9  783.55  508.54788.9422   513.9  798.36   525.9  810.57  600.41843.7339
   613.9  841.82   642.3 842.078   649.9  843.91   669.9  857.89   689.8  868.07
#Mann= 17 ,-1 , 0
       0     .12       0  106.43     .06       0  216.95     .12       0
  223.45    .016       0  307.22     .06       0  341.92    .016       0
   349.1     .06       0  383.58    .016       0  390.99     .12       0
  425.23    .016       0  432.87     .08       0     438    .045       0
  455.68     .08       0  466.89    .016       0  508.54     .12       0
  600.41    .016       0   642.3     .12       0
#XS Ineff= 2 , 0
          267.29  775.41
Permanent Ineff=
       F       F
Bank Sta=438,455.68
XS Rating Curve= 0 ,0
Exp/Cntr=0.3,0.1

Type RM Length L Ch R = 1 ,12582.3 ,130.9,162.4,174.8
XS GIS Cut Line= 3
     1773898.849      429979.096     1773957.877      430121.457
     1774335.655      430501.318
#Sta/Elev= 30
       0  795.47    15.8  785.38    31.6  777.34    47.4  775.75   86.13775.6422
   118.1776.1512  173.16774.2435  215.04773.7247  232.17773.9362  256.93774.2783
  273.82 773.906  298.81773.2318     406   774.2     418  773.62     426  771.43
     434  769.98  443.93771.4172     454  775.11   482.1776.0707   493.9  775.75
   501.9  782.33   513.9   796.5   517.9  800.01   553.9  817.27   605.9  836.75
   617.9  843.61   625.9     845   633.9  844.55  675.78 846.205   689.8   848.2
#Mann= 14 ,-1 , 0
       0     .12       0   86.13     .06       0   118.1     .12       0
  173.16     .06       0  215.04     .12       0  232.17     .06       0
  256.93    .016       0  273.82     .12       0  298.81    .016       0
     426    .045       0  443.93    .016       0   482.1     .12       0
   633.9    .016       0  675.78     .12       0
#XS Ineff= 2 , 0
          261.51  775.54
Permanent Ineff=
       F       F
Bank Sta=426,443.93
XS Rating Curve= 0 ,0
Exp/Cntr=0.3,0.1

Type RM Length L Ch R = 1 ,12419.9 ,234.2,238.1,239.6
XS GIS Cut Line= 2
     1773888.433      429975.971     1774165.516      430678.054
#Sta/Elev= 30
       0  799.65      16  789.03    35.9  778.08   57.14  775.78   64.84775.6935
   88.89 775.543   107.8  776.59  145.29775.5267   191.7  773.46   275.6  773.14
   295.5  771.56   309.7  768.36   323.5  768.51   324.7  768.84   331.5  770.34
  374.67772.0262   427.3  770.32  438.17765.7073   439.3   765.1   443.3  765.15
   455.3  770.32  469.93771.2973   483.2  771.05   495.2  768.77  547.58770.1712
  565.19770.9584  596.94772.1516  628.03773.9954  628.69774.0053   754.8  774.58
#Mann= 16 ,-1 , 0
       0     .12       0   57.14     .06       0   64.84     .12       0
   88.89     .06       0  145.29     .12       0   309.7    .045       0
   323.5    .045       0   324.7     .12       0  374.67     .06       0
  438.17    .016       0  469.93     .12       0  547.58     .08       0
  565.19     .12       0  596.94     .06       0  628.03    .016       0
  628.69     .12       0
#XS Ineff= 2 , 0
                           383.9          773.16
Permanent Ineff=
       F       F
Bank Sta=309.7,323.5
XS Rating Curve= 0 ,0
Exp/Cntr=0.3,0.1

Type RM Length L Ch R = 1 ,12181.8 ,56.6,53.1,52.5
XS GIS Cut Line= 3
     1773746.698      430041.122     1773907.288      430555.879
     1773844.788      430686.087
#Sta/Elev= 30
       0  780.98      12  777.19      28   774.1   49.31773.7061   127.8  771.05
  234.95770.5969   259.6  769.97   283.6  766.22   371.5  764.49   375.5  764.03
  381.45  761.46   383.4  760.56   395.4  761.84     398   762.5  420.59766.4903
  451.52766.6194   491.3  766.76   515.3  767.62   539.2  770.13   554.8  775.76
   570.4   785.9   578.3  789.48   586.1  790.83   609.5  792.93   613.4  794.28
   621.2  799.51   632.9  810.93   644.6   821.2   660.2  831.22   683.7  843.89
#Mann= 8 ,-1 , 0
       0     .12       0   49.31     .06       0  234.95     .12       0
  381.45    .045       0   395.4    .045       0     398     .08       0
  420.59    .016       0  451.52     .12       0
#XS Ineff= 2 , 0
                          447.01          767.31
Permanent Ineff=
       F       F
Bank Sta=381.45,395.4
XS Rating Curve= 0 ,0
Exp/Cntr=0.3,0.1

Type RM Length L Ch R = 1 ,12128.8 ,54,54.2,54.1
XS GIS Cut Line= 3
     1773687.716      430064.434     1773846.158      430527.707
     1773792.686      430679.096
#Sta/Elev= 30
       0  784.29    31.8  777.91   87.54771.7836  118.76770.3076  146.18770.1416
   183.1  772.97     195  769.74   212.4 769.478  237.45 768.875   266.7   768.5
  306.05765.0234  328.72764.5068  337.26764.4571   374.2  763.72     380   761.4
   386.1  759.78     395  761.32  399.69763.5546     406  765.54  430.91766.1149
   485.6  766.68   489.6  767.62   501.4   777.1     521  787.52   536.6  791.42
   552.3  791.35   560.1  793.46   567.9  799.06   595.4   825.7   650.2  855.44
#Mann= 13 ,-1 , 0
       0     .12       0   87.54     .06       0  118.76     .12       0
  146.18     .06       0   212.4    .016       0  237.45     .06       0
  306.05    .016       0  328.72     .12       0  337.26     .06       0
     380    .045       0     395     .06       0  399.69    .016       0
  430.91     .12       0
#XS Ineff= 2 , 0
                          446.44          767.36
Permanent Ineff=
       F       F
Bank Sta=380,395
XS Rating Curve= 0 ,0
Exp/Cntr=0.3,0.1

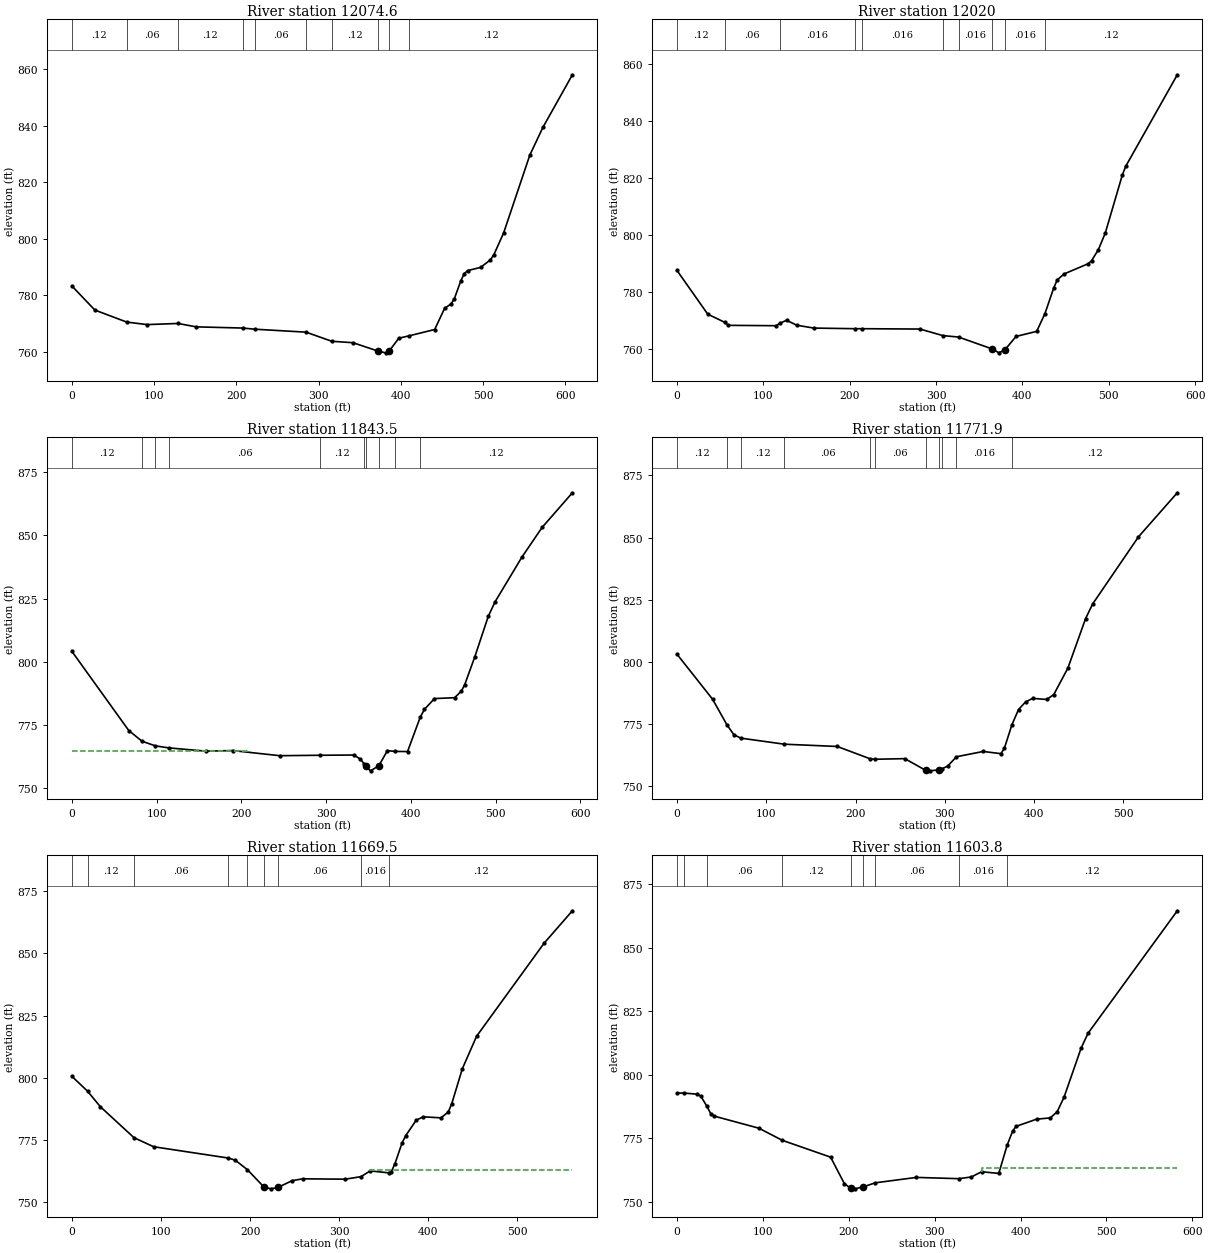
Type RM Length L Ch R = 1 ,12074.6 ,47.2,54.5,61.6
XS GIS Cut Line= 3
     1773638.782      430084.246     1773777.883      430494.657
     1773741.875      430666.387
#Sta/Elev= 30
       0  783.21    27.8  774.71   66.54770.4568    91.4  769.56  128.91769.9627
   151.1  768.76   207.8768.3335  222.47767.9283  284.84766.8781  316.03763.6517
   341.9  763.14  372.02760.1998   381.7  759.55   385.6  760.07   397.6  764.73
  409.59765.5411   441.3  767.82   453.3  775.31   461.3  776.92   465.2  778.72
   473.2  785.18   477.2  787.57   481.2  788.69   497.2  789.84   509.1  792.52
   513.1  794.23   525.1     802     557  829.62   572.9  839.44   608.8   858.1
#Mann= 10 ,-1 , 0
       0     .12       0   66.54     .06       0  128.91     .12       0
   207.8    .016       0  222.47     .06       0  284.84    .016       0
  316.03     .12       0  372.02    .045       0   385.6    .016       0
  409.59     .12       0
Bank Sta=372.02,385.6
XS Rating Curve= 0 ,0
Exp/Cntr=0.3,0.1

Type RM Length L Ch R = 1 ,12020   ,175.4,176.5,177.7
XS GIS Cut Line= 3
      1773599.63      430095.762     1773705.186       430361.04
     1773707.344      430654.876
#Sta/Elev= 30
       0  787.73    35.7  772.37   55.43769.4983    59.5  768.45     115  768.32
  119.01769.1327   126.9  770.22   138.8  768.49   158.6  767.49  206.42767.2767
  214.37767.2728   281.5  767.15  308.02764.8459  326.07764.3478     365  760.18
   372.9  758.81     380  759.96   392.7  764.56   416.6  766.34  426.16772.5851
   436.4  781.64   440.4  784.38   448.3  786.47   476.1  790.04   480.1   791.1
     488  794.98     496   800.8   515.8  821.22   519.8  824.28   579.4   856.3
#Mann= 10 ,-1 , 0
       0     .12       0   55.43     .06       0  119.01    .016       0
  206.42     .12       0  214.37    .016       0  308.02     .12       0
  326.07    .016       0     365    .045       0     380    .016       0
  426.16     .12       0
Bank Sta=365,380
XS Rating Curve= 0 ,0
Exp/Cntr=0.3,0.1

Type RM Length L Ch R = 1 ,11843.5 ,89.5,71.6,53.7
XS GIS Cut Line= 3
     1773494.075      430099.235     1773540.603      430224.929
     1773520.464      430681.179
#Sta/Elev= 30
       0   804.1      67   772.9   82.71768.6447    98.5766.8287   114.2766.0354
   157.9  764.75   189.6  764.98   245.2  762.95  292.81763.1182   332.6  763.22
   340.5  761.61   345.2  759.56  346.88  758.71   352.4  756.97  362.27  758.99
   372.3  764.94   381.5764.6442   396.1  764.58  411.06778.1257     416  781.23
   427.9  785.51   451.7  785.85   459.7  788.48   463.6     791   475.6  802.08
   491.4  817.98   499.4  823.71   531.2  841.42     555  853.12   590.7  866.78
#Mann= 10 ,-1 , 0
       0     .12       0   82.71     .06       0    98.5     .12       0
   114.2     .06       0  292.81     .12       0   345.2    .045       0
  346.88    .045       0  362.27     .06       0   381.5    .016       0
  411.06     .12       0
#XS Ineff= 2 , 0
          210.27  764.83
Permanent Ineff=
       F       F
Bank Sta=346.88,362.27
XS Rating Curve= 0 ,0
Exp/Cntr=0.3,0.1

Type RM Length L Ch R = 1 ,11771.9 ,97.7,102.3,106.2
XS GIS Cut Line= 3
     1773352.459      430154.828     1773488.994      430473.823
     1773514.609       430685.58
#Sta/Elev= 30
       0  803.15    39.9  785.05   56.03774.7355    63.8  770.76   71.49769.4034
  120.28766.9643   179.5  766.05  216.67761.0601  221.62760.9155   255.2  761.16
   278.5  756.47   283.2  756.26   293.5  756.66  296.68757.0494   303.1  758.16
  313.05761.9191     343  764.05   362.8  763.16   366.7  765.37  375.06774.7189
   382.5  780.89   390.4  783.95   398.3  785.37   414.1  784.94     422  786.92
   437.8  797.56   457.6  817.42   465.5   823.3   516.8  850.27   560.3  867.98
#Mann= 11 ,-1 , 0
       0     .12       0   56.03     .06       0   71.49     .12       0
  120.28     .06       0  216.67    .016       0  221.62     .06       0
   278.5    .045       0   293.5    .016       0  296.68     .12       0
  313.05    .016       0  375.06     .12       0
Bank Sta=278.5,293.5
XS Rating Curve= 0 ,0
Exp/Cntr=0.3,0.1

Type RM Length L Ch R = 1 ,11669.5 ,63.6,65.8,68.7
XS GIS Cut Line= 2
     1773285.429      430171.352     1773495.395      430692.239
#Sta/Elev= 30
       0  800.57   17.53794.6054    31.9  788.38   69.56775.9622    91.6  772.32
  175.53767.7711   183.2  766.92  196.94763.0742   215.1  756.25     223   755.4
     231  755.94     247  758.68   258.9  759.43   306.7  759.28  324.32760.2914
   334.6   762.6  356.17761.8124   358.5  762.36   362.5  765.56   370.4  773.79
   374.4   776.7   386.4  783.02   394.3  784.34   414.2  783.93   422.2  786.25
   426.2  789.59   438.1  803.67   454.1  816.73   529.8  854.09   561.6  867.14
#Mann= 9 ,-1 , 0
       0     .06       0   17.53     .12       0   69.56     .06       0
  175.53    .016       0  196.94     .06       0   215.1    .045       0
     231     .06       0  324.32    .016       0  356.17     .12       0
#XS Ineff= 2 , 0
                          334.41           762.8
Permanent Ineff=
       F       F
Bank Sta=215.1,231
XS Rating Curve= 0 ,0
Exp/Cntr=0.3,0.1

Type RM Length L Ch R = 1 ,11603.8 ,147.7,140.2,132.4
XS GIS Cut Line= 3
     1773179.992      430200.658      1773286.91      430318.268
     1773462.952      430703.481
#Sta/Elev= 30
       0  792.79    7.67   792.8    23.8  792.36    27.8  791.59   34.76 787.661
    39.7  784.49    43.7  783.69    95.4  778.97  122.58774.2069   178.9  767.57
   194.9  757.17   202.1  755.35   206.9   755.1   217.1  755.88  230.72757.4614
   278.8   759.6  328.14759.1001   342.7  759.77   354.7  761.83   374.7  761.17
  384.33772.1907   390.7  777.73   394.7  779.67   418.7  782.52   434.6  783.02
   442.6  785.41   450.6  791.12   470.6  810.54   478.6  816.34   582.5  864.54
#Mann= 9 ,-1 , 0
       0     .06       0    7.67     .12       0   34.76     .06       0
  122.58     .12       0   202.1    .045       0   217.1     .12       0
  230.72     .06       0  328.14    .016       0  384.33     .12       0
#XS Ineff= 2 , 0
                          355.42          763.18
Permanent Ineff=
       F       F
Bank Sta=202.1,217.1
XS Rating Curve= 0 ,0
Exp/Cntr=0.3,0.1

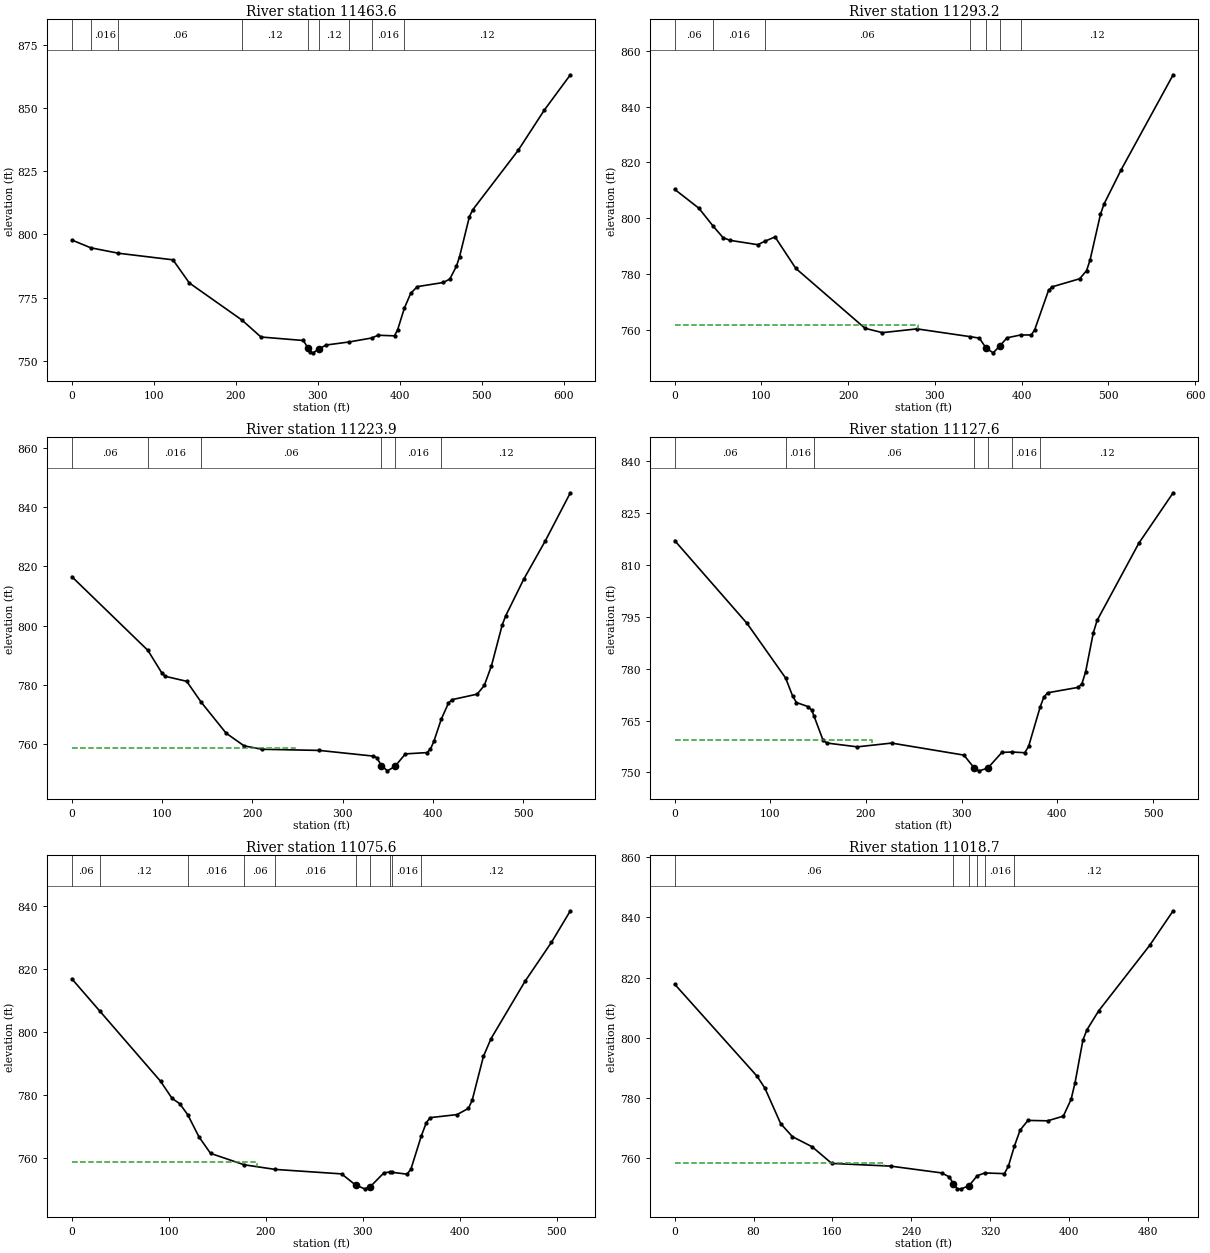
Type RM Length L Ch R = 1 ,11463.6 ,154.6,170.4,186.5
XS GIS Cut Line= 3
     1773135.635      430213.184     1773165.383      430405.768
     1773445.292      430709.601
#Sta/Elev= 30
       0  797.79   22.96794.7217   56.78792.5657   123.3  789.96   143.2  780.82
  207.35766.1567   230.6  759.44   282.3  758.06  287.86755.1435   290.2  753.33
   294.2  753.18     302  754.86   310.1  756.27  338.12757.4811  365.46759.0396
   373.6  760.14   393.5   759.9   397.4   762.4  405.61770.9243   413.3  776.74
   421.3  779.36   453.1     781     461  782.38     469   787.4   472.9  791.27
   484.8  806.95   488.8   809.7   544.4  833.28   576.2  849.16     608  863.14
#Mann= 9 ,-1 , 0
       0     .12       0   22.96    .016       0   56.78     .06       0
  207.35     .12       0  287.86    .045       0     302     .12       0
  338.12     .06       0  365.46    .016       0  405.61     .12       0
Bank Sta=287.86,302
XS Rating Curve= 0 ,0
Exp/Cntr=0.3,0.1

Type RM Length L Ch R = 1 ,11293.2 ,69.1,69.2,69.1
XS GIS Cut Line= 2
      1773108.03       430220.98     1773125.791      430795.401
#Sta/Elev= 30
       0  810.32    27.9  803.55   44.45 797.068    55.9  792.96    63.9  792.02
    95.8  790.46  103.55791.6481   115.7  793.25   139.7  781.93   219.5  760.44
   239.5  758.89   279.4  760.24  339.95  757.48   351.2  756.93   359.2   753.3
   367.2  751.64   375.2  754.24   383.1  757.03  399.05758.0689   411.1  758.04
   415.1  759.96     431  774.06     435  775.32   466.9  778.23   474.9  781.16
   478.9  784.97   490.9  801.37   494.9     805   514.8  817.39   574.7  851.46
#Mann= 7 ,-1 , 0
       0     .06       0   44.45    .016       0  103.55     .06       0
  339.95     .12       0   359.2    .045       0   375.2    .016       0
  399.05     .12       0
#XS Ineff= 2 , 0
           280.5  761.49
Permanent Ineff=
       F       F
Bank Sta=359.2,375.2
XS Rating Curve= 0 ,0
Exp/Cntr=0.3,0.1

Type RM Length L Ch R = 1 ,11223.9 ,96.5,96.4,96.3
XS GIS Cut Line= 2
     1773039.617      430240.301     1773056.689      430792.429
#Sta/Elev= 30
       0   816.5   84.22791.6489    99.4  784.17   103.3  782.92   127.2  781.22
  143.32774.1584   170.9  763.73   190.8  759.45   210.6   758.3   274.2  757.91
   333.8     756   337.8  755.48   343.1  752.77   349.7  751.02   358.1  752.54
   369.6  756.74   393.4  757.17   397.4  758.35   401.4   761.2  409.27768.3932
   417.3  773.86   421.2  775.03   449.1  776.89     457  779.81     465  786.48
   476.9  800.26   480.9  803.42   500.7  815.64   524.6  828.58   552.4  844.82
#Mann= 6 ,-1 , 0
       0     .06       0   84.22    .016       0  143.32     .06       0
   343.1    .045       0   358.1    .016       0  409.27     .12       0
#XS Ineff= 2 , 0
          247.02  758.76
Permanent Ineff=
       F       F
Bank Sta=343.1,358.1
XS Rating Curve= 0 ,0
Exp/Cntr=0.3,0.1

Type RM Length L Ch R = 1 ,11127.6 ,55.6,51.9,48.3
XS GIS Cut Line= 2
     1772942.753      430267.656     1772961.348      430788.329
#Sta/Elev= 30
       0  817.09    75.6  793.14  115.97777.3162   123.3  772.09   127.3  770.24
   139.2  769.08   143.2  768.04  145.52766.3928   155.1   759.3   159.1  758.52
   190.9  757.42   226.7  758.51   302.3  755.03  313.22751.2475   318.2  750.48
   327.2  751.27     342  755.81  352.41755.9279   365.9  755.72   369.9  757.54
  381.96768.9288   385.8  771.78   389.8  773.06   421.6  774.62   425.6  775.65
   429.5  779.12   437.5  790.36   441.5  793.99   485.2  816.37     521  830.92
#Mann= 7 ,-1 , 0
       0     .06       0  115.97    .016       0  145.52     .06       0
  313.22    .045       0   327.2     .12       0  352.41    .016       0
  381.96     .12       0
#XS Ineff= 2 , 0
          206.19  759.43
Permanent Ineff=
       F       F
Bank Sta=313.22,327.2
XS Rating Curve= 0 ,0
Exp/Cntr=0.3,0.1

Type RM Length L Ch R = 1 ,11075.6 ,56.3,56.9,57.5
XS GIS Cut Line= 3
     1772843.596      430296.038     1772920.808      430681.636
     1772907.761      430801.668
#Sta/Elev= 30
       0  816.87   29.01806.5563    91.4  784.35   103.3   778.9   111.2  777.22
  119.37773.7537   131.1  766.64     143  761.43  177.67 757.808  209.74756.3373
   278.1  754.92   292.6  751.36   301.9  750.17   307.6  750.84   321.8  755.26
  328.11755.5195  330.23755.4201   345.6  754.83   349.6  756.44  360.35767.0045
   365.4  771.15   369.4  772.79   397.2  773.76   408.8  775.72   412.7  778.24
   424.4  792.29   432.2  797.89   467.2  816.08   494.5  828.48     514  838.51
#Mann= 10 ,-1 , 0
       0     .06       0   29.01     .12       0  119.37    .016       0
  177.67     .06       0  209.74    .016       0   292.6    .045       0
   307.6    .016       0  328.11     .12       0  330.23    .016       0
  360.35     .12       0
#XS Ineff= 2 , 0
          190.71  758.58
Permanent Ineff=
       F       F
Bank Sta=292.6,307.6
XS Rating Curve= 0 ,0
Exp/Cntr=0.3,0.1

Type RM Length L Ch R = 1 ,11018.7 ,56.1,53.9,51.7
XS GIS Cut Line= 2
     1772796.968      430309.536     1772882.609      430808.272
#Sta/Elev= 30
       0  817.79    83.7   787.2    91.6  783.23   107.6  771.46   119.5  767.14
   139.5  763.78   159.4  758.25   219.2  757.35     271  755.09   278.9  753.74
   282.9  751.43   286.9  749.84   290.9   749.8   298.8  750.83  307.12754.1672
  314.84755.0803   334.7  754.85   338.7  757.29  344.81763.9459   350.6  769.29
   358.6  772.54   378.5   772.4   394.5  773.95   402.4  779.54   406.4  785.06
   414.4  799.24   418.4  802.61   430.3   808.9   482.1  830.68     506   842.2
#Mann= 6 ,-1 , 0
       0     .06       0   282.9    .045       0   298.8     .06       0
  307.12     .12       0  314.84    .016       0  344.81     .12       0
#XS Ineff= 2 , 0
          212.38  758.45
Permanent Ineff=
       F       F
Bank Sta=282.9,298.8
XS Rating Curve= 0 ,0
Exp/Cntr=0.3,0.1

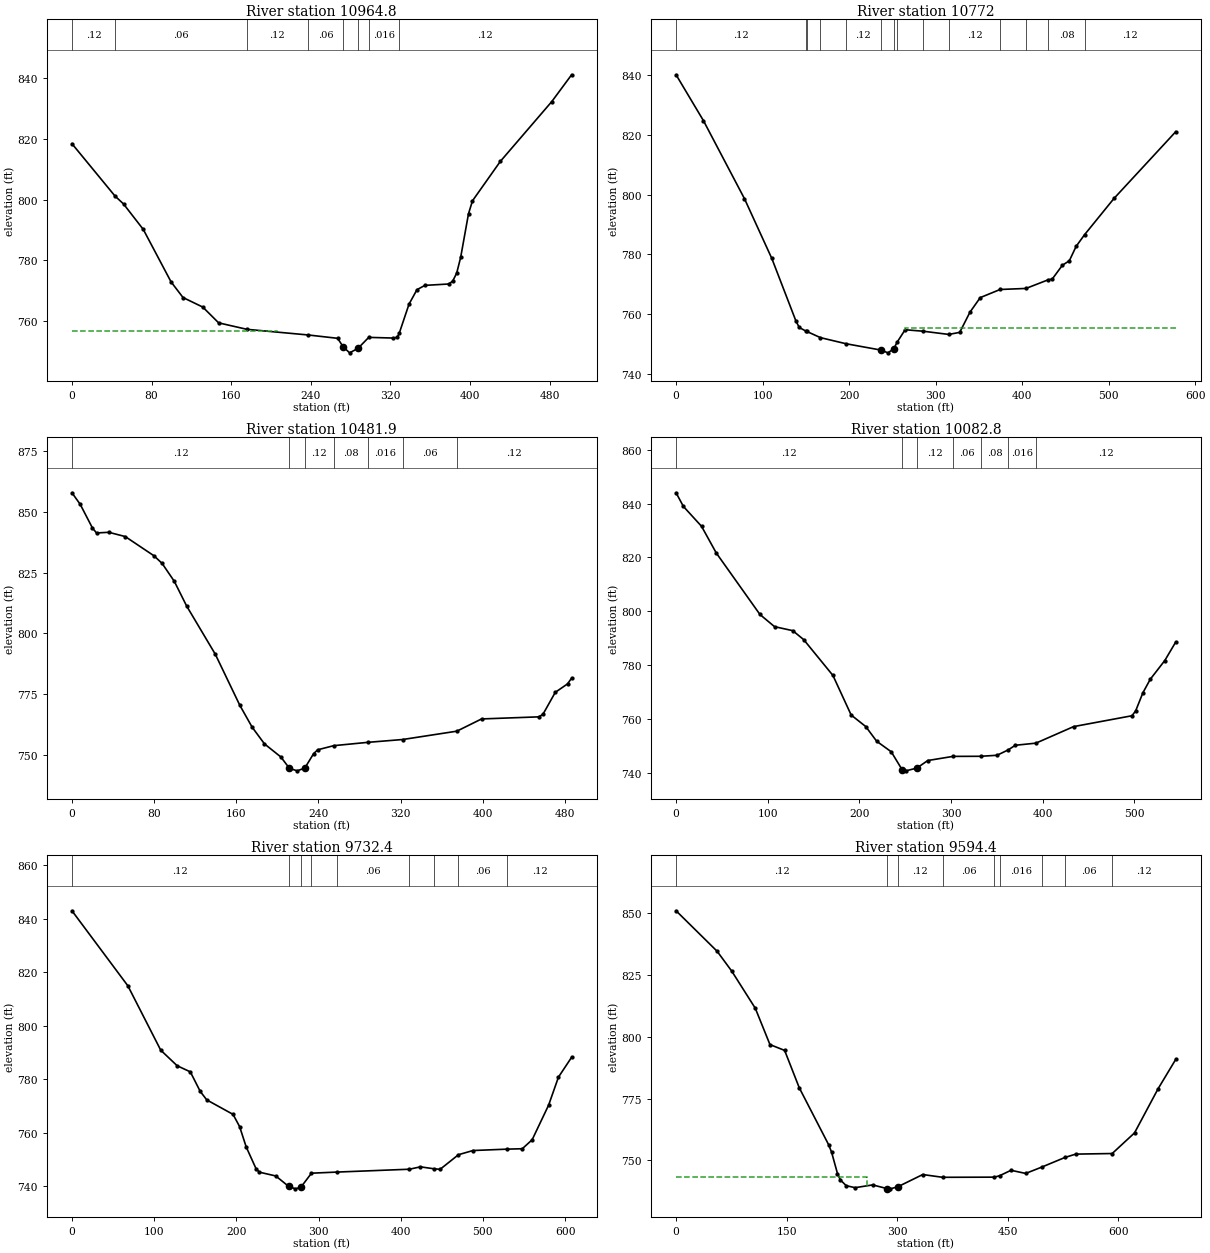
Type RM Length L Ch R = 1 ,10964.8 ,184.7,192.8,200.8
XS GIS Cut Line= 2
     1772719.502       430331.96     1772850.705      430816.649
#Sta/Elev= 30
       0  818.45   43.25801.1833    51.8  798.58    71.7  790.15    99.6  772.85
   111.6   767.7   131.5  764.54   147.4  759.34  175.84757.2073  237.04755.3564
     267  754.24   272.4   751.5     279  749.45   287.4  750.92  298.24754.5529
   322.8  754.33   326.8  754.53  328.84 755.856   338.7  765.51   346.7  770.29
   354.7  771.71   378.6  772.16   382.6  773.12   386.6  775.74   390.6  780.93
   398.5  795.37   402.5  799.62   430.4  812.58   482.2  832.36   502.1  841.19
#Mann= 8 ,-1 , 0
       0     .12       0   43.25     .06       0  175.84     .12       0
  237.04     .06       0   272.4    .045       0   287.4     .06       0
  298.24    .016       0  328.84     .12       0
#XS Ineff= 2 , 0
          206.48  756.66
Permanent Ineff=
       F       F
Bank Sta=272.4,287.4
XS Rating Curve= 0 ,0
Exp/Cntr=0.3,0.1

Type RM Length L Ch R = 1 ,10772   ,304.3,290.1,275.2
XS GIS Cut Line= 4
     1772537.412       430384.67     1772612.735      430514.709
       1772590.6      430742.573     1772763.637       430839.51
#Sta/Elev= 30
       0  840.19    31.6  824.84    79.1  798.66   110.7  778.64   138.4  757.81
   142.4  755.52  150.13754.3145  151.07754.2072  166.88 752.124  196.55750.0762
   236.6  747.97     245  747.03   251.6  748.42   255.9750.7615   264.8  754.77
  285.58754.2745  315.25753.1984   327.9  753.89   339.7  760.63   351.6  765.53
   374.6768.2567   404.5768.6063  430.25771.5097   434.8  771.73   446.6  776.38
   454.6  777.87   462.5  782.71  472.21786.6097   506.2  798.74   577.6  821.11
#Mann= 14 ,-1 , 0
       0     .12       0  150.13     .06       0  151.07     .12       0
  166.88     .06       0  196.55     .12       0   236.6    .045       0
   251.6     .12       0   255.9     .08       0  285.58    .016       0
  315.25     .12       0   374.6     .06       0   404.5     .12       0
  430.25     .08       0  472.21     .12       0
#XS Ineff= 2 , 0
                          265.02           755.2
Permanent Ineff=
       F       F
Bank Sta=236.6,251.6
XS Rating Curve= 0 ,0
Exp/Cntr=0.3,0.1

Type RM Length L Ch R = 1 ,10481.9 ,392.4,399,405.7
XS GIS Cut Line= 2
     1772257.441      430484.045     1772488.547      430912.307
#Sta/Elev= 30
       0  857.89       8  853.16    19.9  843.45    23.9  841.36    35.9  841.63
    51.9  839.88    79.8  831.99    87.8  828.84    99.7  821.44   111.7  811.29
   139.6  791.47   163.5  770.44   175.5  761.44   187.5  754.58   203.4  749.22
   211.8  744.53   219.4   743.5   226.8  744.66   235.3  750.55   239.3  752.16
  254.99753.8584  288.55755.2379  322.11756.3882  374.82759.8155   398.9  764.85
   454.7  765.71   458.7  766.76   470.7   775.8   482.6  779.26   486.6  781.63
#Mann= 7 ,-1 , 0
       0     .12       0   211.8    .045       0   226.8     .12       0
  254.99     .08       0  288.55    .016       0  322.11     .06       0
  374.82     .12       0
Bank Sta=211.8,226.8
XS Rating Curve= 0 ,0
Exp/Cntr=0.3,0.1

Type RM Length L Ch R = 1 ,10082.8 ,348.9,350.4,351.9
XS GIS Cut Line= 2
     1771927.831      430530.515     1772036.015      431064.689
#Sta/Elev= 30
       0  843.99       8  838.92    27.8  831.55    43.8  821.69    91.5  798.86
   107.4  794.35   127.3  792.86   139.2  789.54   171.1  776.26     191  761.58
   206.9  757.31   218.8  751.87   234.7  747.96   246.6  741.29   250.6  740.89
   262.6   741.9   274.5  744.71  302.08746.2492  332.22746.2847   350.1  746.66
  362.36748.6689     370  750.37  392.49751.1554   433.6  757.29   497.3  761.32
   501.3  763.12   509.2  769.83   517.2  774.83   533.1   781.8     545  788.64
#Mann= 7 ,-1 , 0
       0     .12       0   246.6    .045       0   262.6     .12       0
  302.08     .06       0  332.22     .08       0  362.36    .016       0
  392.49     .12       0
Bank Sta=246.6,262.6
XS Rating Curve= 0 ,0
Exp/Cntr=0.3,0.1

Type RM Length L Ch R = 1 ,9732.4  ,143.8,137.9,132.1
XS GIS Cut Line= 2
     1771594.477      430537.842     1771676.609      431140.137
#Sta/Elev= 30
       0  842.97      68  814.91     108  790.83     128     785     144  782.72
     156  775.44     164  772.23     196  766.81     204  762.22     212  754.62
     224  746.47     228   745.2     248  743.77   263.6  739.88   271.9  738.96
   278.6   739.6  291.42 744.816  321.95745.2251  410.66746.2994   423.9  747.19
  440.47746.4603   447.9  746.26  470.27751.7311   487.9  753.29  529.89753.8149
   547.9  753.96   559.9  757.32   579.9  770.25   591.9  780.75   607.9  788.17
#Mann= 9 ,-1 , 0
       0     .12       0   263.6    .045       0   278.6     .12       0
  291.42     .08       0  321.95     .06       0  410.66    .016       0
  440.47     .12       0  470.27     .06       0  529.89     .12       0
Bank Sta=263.6,278.6
XS Rating Curve= 0 ,0
Exp/Cntr=0.3,0.1

Type RM Length L Ch R = 1 ,9594.4  ,95.5,99.8,103.9
XS GIS Cut Line= 3
     1771516.094       430534.81     1771465.336      430747.792
     1771640.598       431172.09
#Sta/Elev= 30
       0  850.97    55.7   834.6    75.6  826.54   107.5  811.55   127.4  796.86
   147.3  794.51   167.2  779.37     207  756.38     211  753.37     219  744.73
   222.9  742.14   230.9  739.81   242.9     739   266.8  740.12   286.2  738.63
   290.8  738.53   301.2  739.41   334.7  744.31  361.69743.1953  432.03743.2565
  439.06743.8382   454.5  746.03   474.4  744.76  495.94747.2902   527.9 751.244
   542.3  752.57  591.81752.8107   622.1  761.15   654.1  779.02     678  790.86
#Mann= 9 ,-1 , 0
       0     .12       0   286.2    .045       0   301.2     .12       0
  361.69     .06       0  432.03     .08       0  439.06    .016       0
  495.94     .12       0   527.9     .06       0  591.81     .12       0
#XS Ineff= 2 , 0
          259.34  743.41
Permanent Ineff=
       F       F
Bank Sta=286.2,301.2
XS Rating Curve= 0 ,0
Exp/Cntr=0.3,0.1