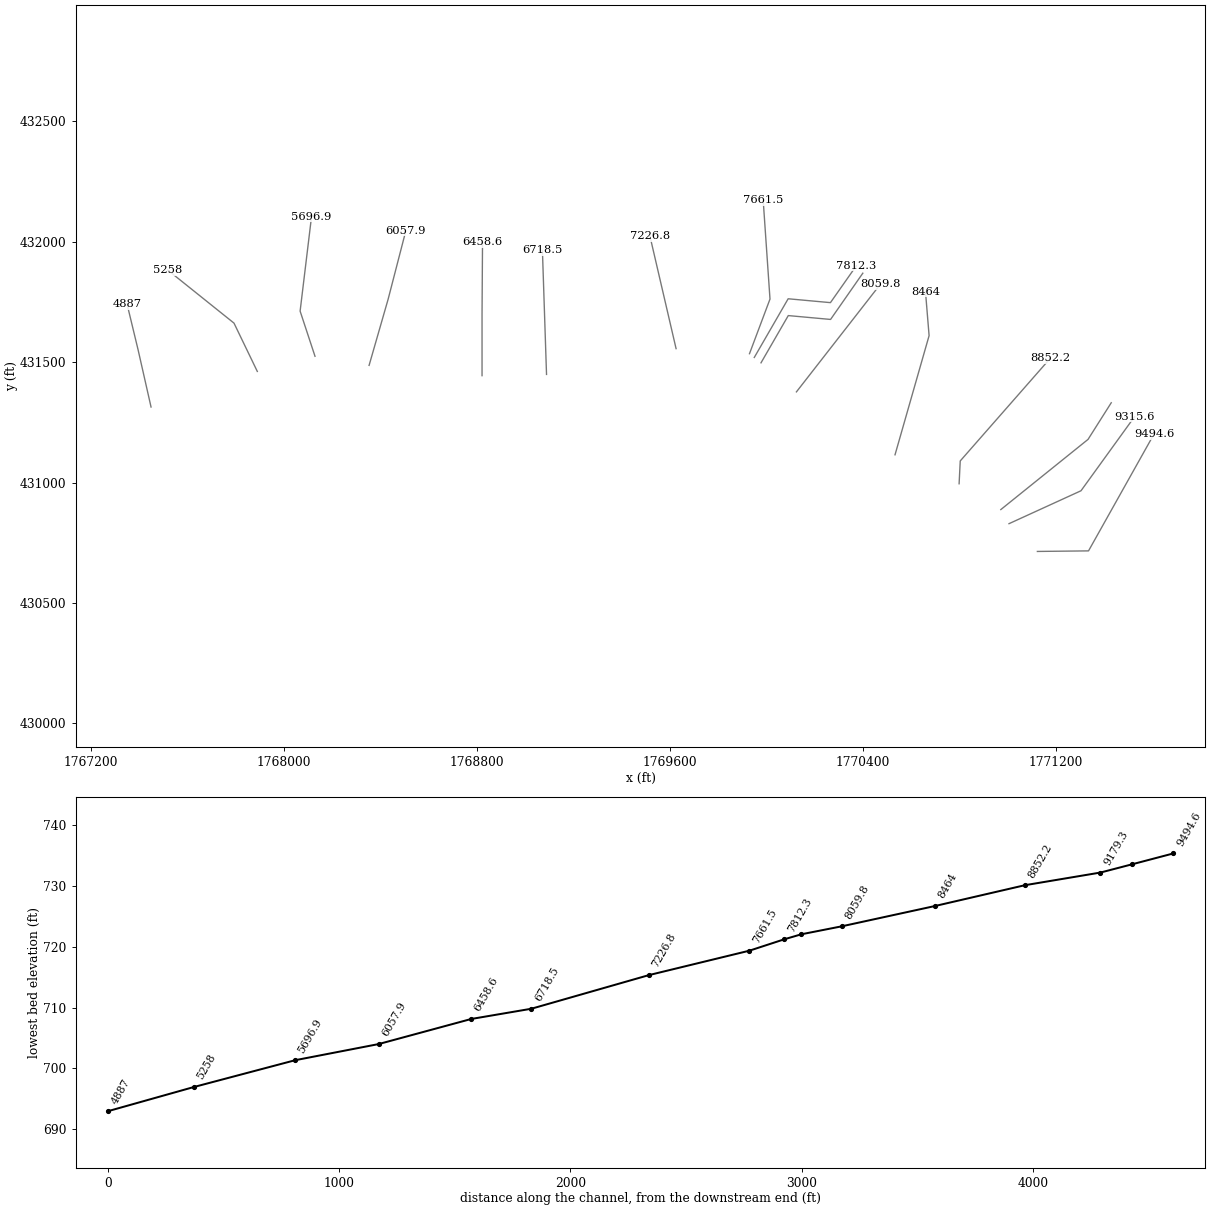
HEC-RAS study LICKCK.prj: LICKCK

--- LICKCK.g01 (geometry) --- (continued)

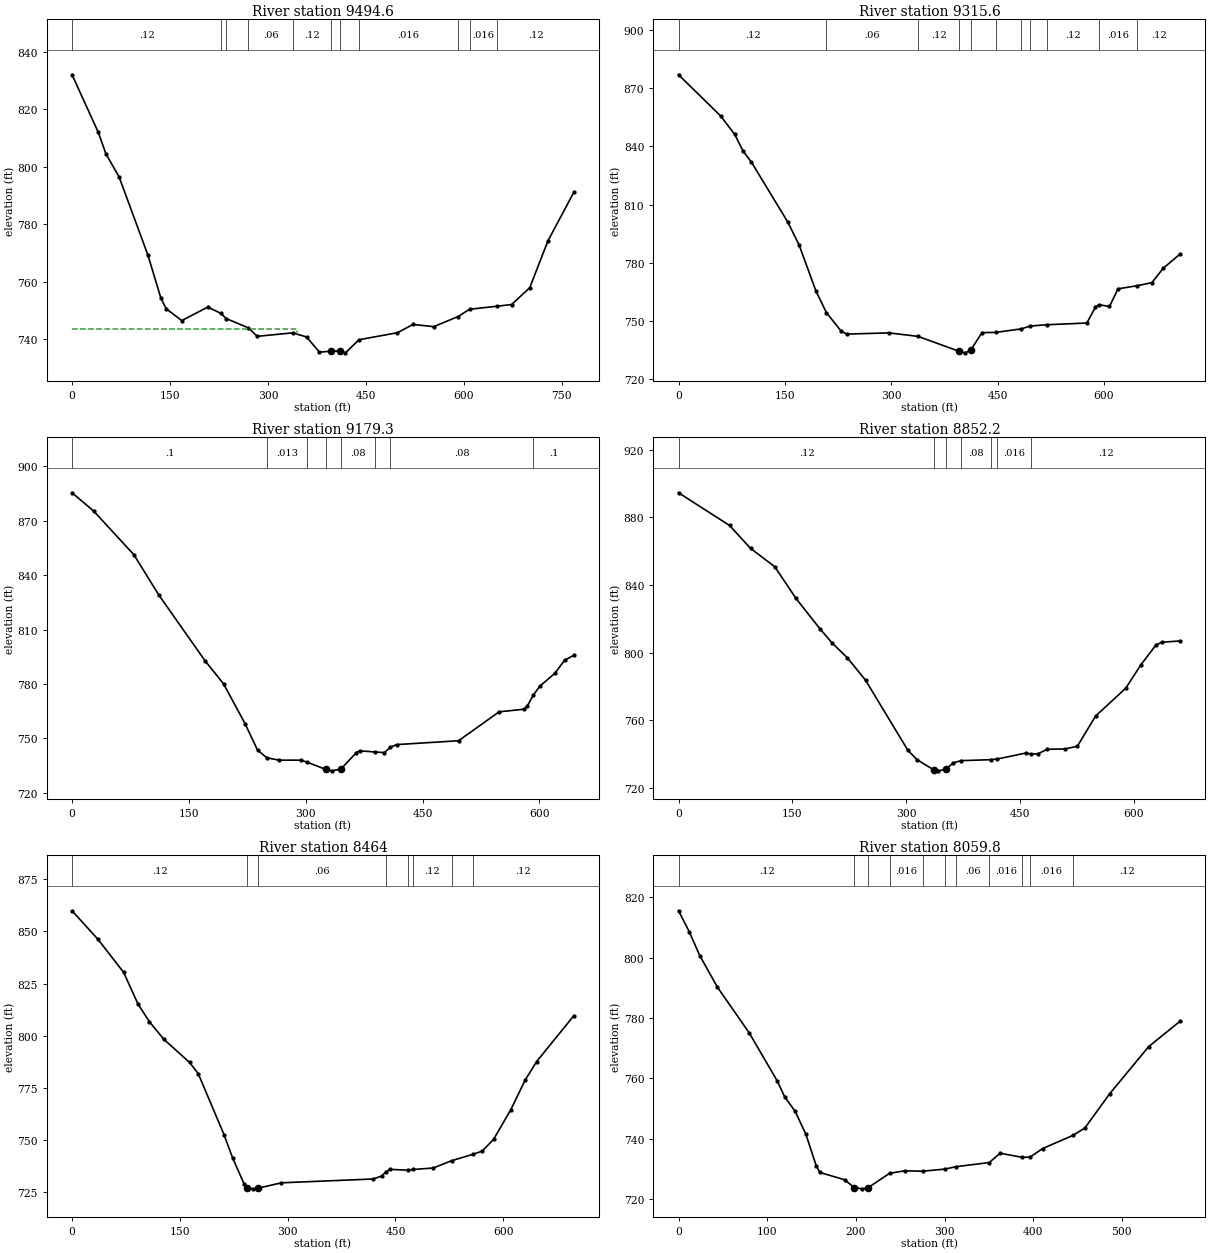
Type RM Length L Ch R = 1 ,9494.6  ,189.4,179.1,168.7
XS GIS Cut Line= 3
     1771122.965      430714.414     1771334.882      430716.749
     1771606.501      431202.345
#Sta/Elev= 30
       0  832.06      40   812.1      52  804.46      72  796.52     116  769.38
     136  754.35     144  750.66   167.9  746.52   207.9  751.22  227.78749.0254
  236.26747.1956   270.1743.9539   283.5  741.03  337.79742.2542     359  740.82
   378.8  735.51   395.7  735.87   410.7  735.89   418.6  735.29  439.31739.8488
   498.1  742.29   521.9  745.17   553.7   744.4   590.8747.8948  608.52750.4452
   651.3 751.535     673   752.1   700.8  757.97   728.6  774.26   768.3  791.18
#Mann= 11 ,-1 , 0
       0     .12       0  227.78    .016       0  236.26     .12       0
   270.1     .06       0  337.79     .12       0   395.7    .045       0
   410.7     .12       0  439.31    .016       0   590.8     .06       0
  608.52    .016       0   651.3     .12       0
#XS Ineff= 2 , 0
          344.27  743.51
Permanent Ineff=
       F       F
Bank Sta=395.7,410.7
XS Rating Curve= 0 ,0
Exp/Cntr=0.3,0.1

Type RM Length L Ch R = 1 ,9315.6  ,142.7,136.3,130.2
XS GIS Cut Line= 3
     1771005.333      430829.722     1771303.727       430966.44
      1771525.68      431274.059
#Sta/Elev= 30
       0     877    59.3  855.79    79.1  846.29      91  837.65   102.8   831.9
   154.2   800.9     170  789.18   193.8  765.35  208.56  754.21   229.4  744.71
   237.3  743.17   296.6   743.8  337.88 741.988   396.1  734.22   404.1   733.5
   412.1  734.92     428  743.93  447.14744.0422  483.56745.8762  495.65  747.32
  519.98748.0208   575.8  748.89   587.8  756.99  592.82758.3419   607.7  757.43
   619.7  766.53  647.08768.1663   667.6  769.74   683.6   777.2   707.6  784.58
#Mann= 11 ,-1 , 0
       0     .12       0  208.56     .06       0  337.88     .12       0
   396.1    .045       0   412.1    .016       0  447.14     .06       0
  483.56     .12       0  495.65     .06       0  519.98     .12       0
  592.82    .016       0  647.08     .12       0
Bank Sta=396.1,412.1
XS Rating Curve= 0 ,0
Exp/Cntr=0.3,0.1

Type RM Length L Ch R = 1 ,9179.3  ,322.8,327.1,331.1
XS GIS Cut Line= 3
      1770971.44      430888.292     1771332.902      431179.774
     1771429.048      431331.904
#Sta/Elev= 30
       0  885.35    27.8  875.25    79.4  851.21   111.1  829.21   170.7  792.81
   194.5  780.08   222.2  758.09   238.1  743.62     250  739.33   265.9  738.04
   293.7  738.04   301.6  736.96   325.7  732.96   333.4  732.15   345.3  733.16
   365.1  742.25   369.1  743.18   388.9  742.55   400.8  742.21   408.8  745.13
   416.7   746.6   496.3  748.73   548.3  764.66   580.3   766.1   584.3  767.72
   592.3   773.9   600.3  778.67   620.3  786.04   632.3  793.08   644.3  795.81
#Mann= 8 ,-1 , 0
       0      .1       0     250    .013       0   301.6     .08       0
   325.7    .045       0   345.3     .08       0   388.9    .013       0
   408.8     .08       0   592.3      .1       0
Bank Sta=325.7,345.3
XS Rating Curve= 0 ,0
Exp/Cntr=0.3,0.1

Type RM Length L Ch R = 1 ,8852.2  ,378.2,388.2,398.1
XS GIS Cut Line= 3
      1770798.56      430995.483     1770803.273      431090.306
     1771176.485      431516.634
#Sta/Elev= 30
       0  894.56    67.2  875.25    94.9  861.69   126.9   850.8   154.8  832.11
   186.7  813.96   202.7  805.61   222.6  796.94   246.6  783.67   302.4  742.19
   314.4  736.71   337.3  730.41   342.3  730.07   352.3  730.92   362.3  734.81
  372.52736.0967  411.77736.6728  420.52737.1015     458   740.6  465.36739.9792
     474  740.15     486  742.82   509.9  743.03   525.9  744.64   549.8  762.44
   589.7  778.98   609.7  792.86   629.6  804.59   637.6  806.17   661.6  806.91
#Mann= 7 ,-1 , 0
       0     .12       0   337.3    .045       0   352.3     .12       0
  372.52     .08       0  411.77     .06       0  420.52    .016       0
  465.36     .12       0
Bank Sta=337.3,352.3
XS Rating Curve= 0 ,0
Exp/Cntr=0.3,0.1

Type RM Length L Ch R = 1 ,8464    ,412.8,404.1,395.3
XS GIS Cut Line= 3
     1770533.021       431115.82     1770674.217      431610.607
     1770659.192      431793.658
#Sta/Elev= 30
       0  859.85    35.9  846.24    71.8  830.33    91.7  815.18   107.7  806.68
   127.6  798.32   163.5   787.2   175.5  781.88   211.4  752.64   223.4  741.46
   239.3  729.07   243.3  727.17   251.3  726.66   259.3     727   291.2  729.55
   418.8  731.37   430.8  732.78  436.38734.8212   442.7  735.99   467.1735.6021
  474.74735.9252   502.6  736.65  528.03740.1301  557.67743.1908   570.4  744.71
   586.4  750.31   610.4  764.52   630.3  778.64   646.3  787.59   698.2  809.61
#Mann= 8 ,-1 , 0
       0     .12       0   243.3    .045       0   259.3     .06       0
  436.38    .016       0   467.1     .06       0  474.74     .12       0
  528.03     .06       0  557.67     .12       0
Bank Sta=243.3,259.3
XS Rating Curve= 0 ,0
Exp/Cntr=0.3,0.1

Type RM Length L Ch R = 1 ,8059.8  ,197.3,173.8,150.3
XS GIS Cut Line= 2
     1770124.407      431377.032     1770471.928      431823.689
#Sta/Elev= 30
       0  815.51      12  808.62    23.9  800.66    43.8  790.21    79.7  775.03
   111.6  758.96   119.6  753.88   131.5  749.01   143.5   741.5   155.4  730.86
   159.4  728.76   187.3  726.32   198.3  723.73   207.2  723.32   213.3  723.61
  238.14728.4904   255.1  729.29  275.56  729.18  300.39729.8657  312.99730.6643
  350.41732.0326   362.7  735.12  387.83733.7562  396.58733.8676   410.5  736.66
  444.68741.0279   458.3  743.51   486.2  754.83   530.1  770.44   565.9  778.97
#Mann= 11 ,-1 , 0
       0     .12       0   198.3    .045       0   213.3     .06       0
  238.14    .016       0  275.56     .06       0  300.39     .12       0
  312.99     .06       0  350.41    .016       0  387.83     .12       0
  396.58    .016       0  444.68     .12       0
Bank Sta=198.3,213.3
XS Rating Curve= 0 ,0
Exp/Cntr=0.3,0.1

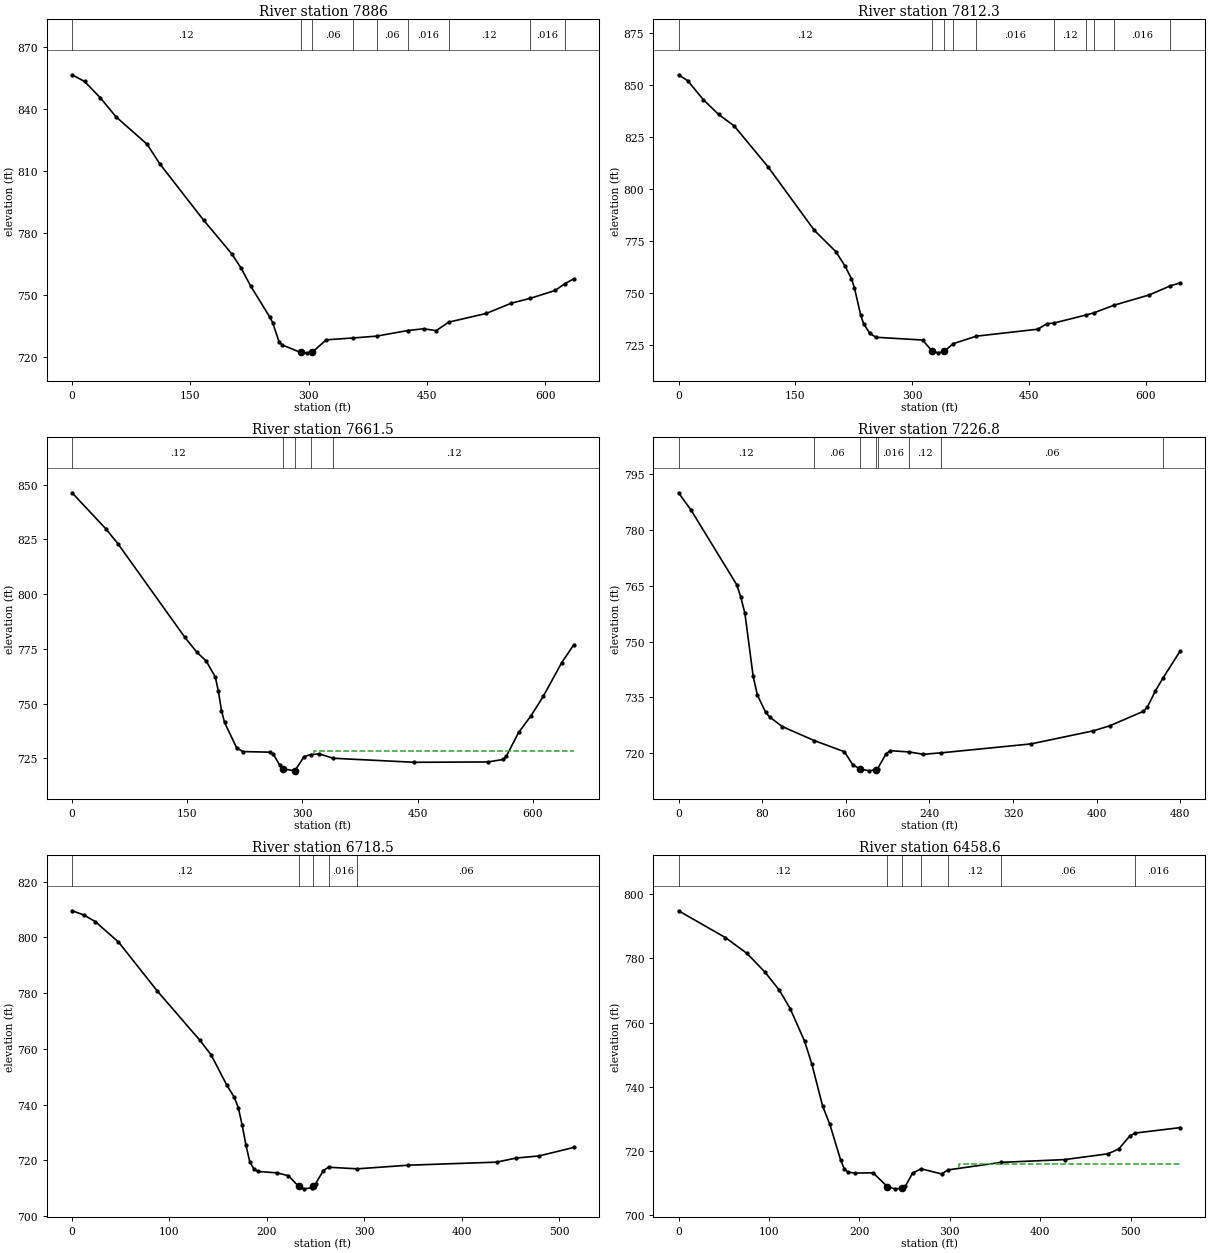
Type RM Length L Ch R = 1 ,7886    ,74.8,73.7,74.4
XS GIS Cut Line= 4
     1769977.664      431497.737     1770090.678      431693.914
     1770265.898       431677.87     1770399.532      431869.956
#Sta/Elev= 30
       0  856.74    15.9   853.5    35.8   845.6    55.6  836.43    95.3  823.02
   111.2   813.6   166.8  786.31   202.6  769.95   214.5  763.01   226.4  754.47
   250.4  739.56   254.4  736.69   262.4  727.42   266.4  725.85   289.9  722.22
   298.4  722.02   304.9  722.45   322.4  728.32  356.52729.2312  386.18730.1101
  425.87732.8369     446  733.69   461.8  732.76  477.59736.8758   525.3  741.11
     557  746.06  581.03748.4182   612.6  752.23  624.64  755.44   636.4  757.88
#Mann= 9 ,-1 , 0
       0     .12       0   289.9    .045       0   304.9     .06       0
  356.52    .016       0  386.18     .06       0  425.87    .016       0
  477.59     .12       0  581.03    .016       0  624.64     .12       0
Bank Sta=289.9,304.9
XS Rating Curve= 0 ,0
Exp/Cntr=0.3,0.1

Type RM Length L Ch R = 1 ,7812.3  ,109.2,150.8,190.7
XS GIS Cut Line= 4
     1769949.786       431520.04     1770090.157      431763.706
     1770265.377      431747.662     1770372.668      431900.787
#Sta/Elev= 30
       0  854.72    11.9  851.83    31.7  842.82    51.5  835.65    71.3  830.22
   114.9  810.52   174.3  780.03     202  769.76   213.9  762.75   221.8  756.87
   225.8   752.4   233.7  739.45   237.6  735.16   245.6   730.5   253.5  728.68
   313.2  727.36   325.2  722.18   333.2   721.2   341.2  721.95  352.53725.5892
  382.19729.1988   461.1  732.55   473.1  735.23  481.48735.4688  522.62739.3302
  532.95740.3781  558.68744.0312   604.4  749.03  630.81753.2972   644.1  754.84
#Mann= 10 ,-1 , 0
       0     .12       0   325.2    .045       0   341.2     .12       0
  352.53     .06       0  382.19    .016       0  481.48     .12       0
  522.62    .016       0  532.95     .12       0  558.68    .016       0
  630.81     .12       0
Bank Sta=325.2,341.2
XS Rating Curve= 0 ,0
Exp/Cntr=0.3,0.1

Type RM Length L Ch R = 1 ,7661.5  ,430.8,434.7,438
XS GIS Cut Line= 3
     1769929.927      431535.652     1770014.896      431762.491
     1769986.688      432172.794
#Sta/Elev= 30
       0  846.31    43.7  829.96    59.6   823.1   146.9  780.29   162.8  773.38
   174.7  769.48   186.6   762.1   190.6   755.6   194.6  746.79   198.6  741.41
   214.4  729.81   222.4  728.13   258.2  727.85   262.2  726.86   270.2  722.08
     275  720.26     290  719.33   302.1  725.78  310.71 726.749   322.1  727.05
  340.31  725.07   445.9  723.23   541.7  723.39   561.7  724.54   565.7  726.09
   581.6  736.85   597.6  744.45   613.6   753.3   637.5  768.64   653.5  776.96
#Mann= 5 ,-1 , 0
       0     .12       0     275    .045       0     290     .08       0
  310.71    .016       0  340.31     .12       0
#XS Ineff= 2 , 0
                          314.96          728.38
Permanent Ineff=
       F       F
Bank Sta=275,290
XS Rating Curve= 0 ,0
Exp/Cntr=0.3,0.1

Type RM Length L Ch R = 1 ,7226.8  ,512.7,508.3,503.9
XS GIS Cut Line= 2
     1769625.727      431556.582      1769517.28       432024.26
#Sta/Elev= 30
       0  789.91    11.9   785.3    55.6  765.28    59.5  762.01    63.5  757.54
    71.4   740.7    75.4  735.68    83.3  731.03    87.3  729.73    99.2   727.2
   129.9723.4377   158.7  720.45   166.6  716.99   173.5  715.82   182.5  715.32
   188.5  715.64  190.54 715.934   198.4  719.81   202.4  720.73  220.86720.3735
   234.1  719.77  251.18720.1472   337.2  722.54   396.8  726.05   412.6   727.4
   444.4  731.24   448.4  732.33   456.3   736.8  463.42740.1651   480.1  747.53
#Mann= 8 ,-1 , 0
       0     .12       0   129.9     .06       0   173.5    .045       0
   188.5     .06       0  190.54    .016       0  220.86     .12       0
  251.18     .06       0  463.42     .12       0
Bank Sta=173.5,188.5
XS Rating Curve= 0 ,0
Exp/Cntr=0.3,0.1

Type RM Length L Ch R = 1 ,6718.5  ,260.6,259.9,259.1
XS GIS Cut Line= 3
     1769088.837      431449.537     1769080.057      431715.135
      1769071.82      431964.317
#Sta/Elev= 30
       0  809.53    11.9  808.06    23.8  805.66    47.6  798.35    87.3  780.83
   130.9   763.2   142.8  757.82   158.6  747.13   166.6  742.57   170.6  738.94
   174.5  732.83   178.5  725.46   182.4  719.53   186.4  717.02   190.4  716.04
   210.2  715.54   222.1  714.51   232.6  710.69     238   709.8   245.9  710.15
   247.6  710.75   249.9  711.57   257.8  716.29  263.27717.5578  292.82 716.976
   344.9  718.27   435.9  719.38   455.7  720.84   479.4   721.6   515.1  724.66
#Mann= 5 ,-1 , 0
       0     .12       0   232.6    .045       0   247.6     .08       0
  263.27    .016       0  292.82     .06       0
Bank Sta=232.6,247.6
XS Rating Curve= 0 ,0
Exp/Cntr=0.3,0.1

Type RM Length L Ch R = 1 ,6458.6  ,407.1,400.7,394.7
XS GIS Cut Line= 3
     1768821.626      431444.345     1768821.627      431703.231
     1768823.604      431999.154
#Sta/Elev= 30
       0  794.87    51.8  786.51    75.7  781.56    95.6  775.73   111.5  770.06
   123.5  764.32   139.4  754.15   147.4  747.04   159.3  733.95   167.3  728.22
   179.2  717.16   183.2  714.35   187.2  713.36   195.2  713.03   215.1  713.12
     231  708.79     239  708.12   246.9  708.27   250.9  709.01   258.9  713.06
  268.32  714.36   290.9  712.76  297.85714.0247  356.93716.3849   426.8  717.24
   474.8  719.05   486.8  720.57   498.8  724.57  504.61725.5167   554.8  727.22
#Mann= 7 ,-1 , 0
       0     .12       0     231    .045       0   246.9     .08       0
  268.32    .016       0  297.85     .12       0  356.93     .06       0
  504.61    .016       0
#XS Ineff= 2 , 0
                          310.22          715.88
Permanent Ineff=
       F       F
Bank Sta=231,246.9
XS Rating Curve= 0 ,0
Exp/Cntr=0.3,0.1

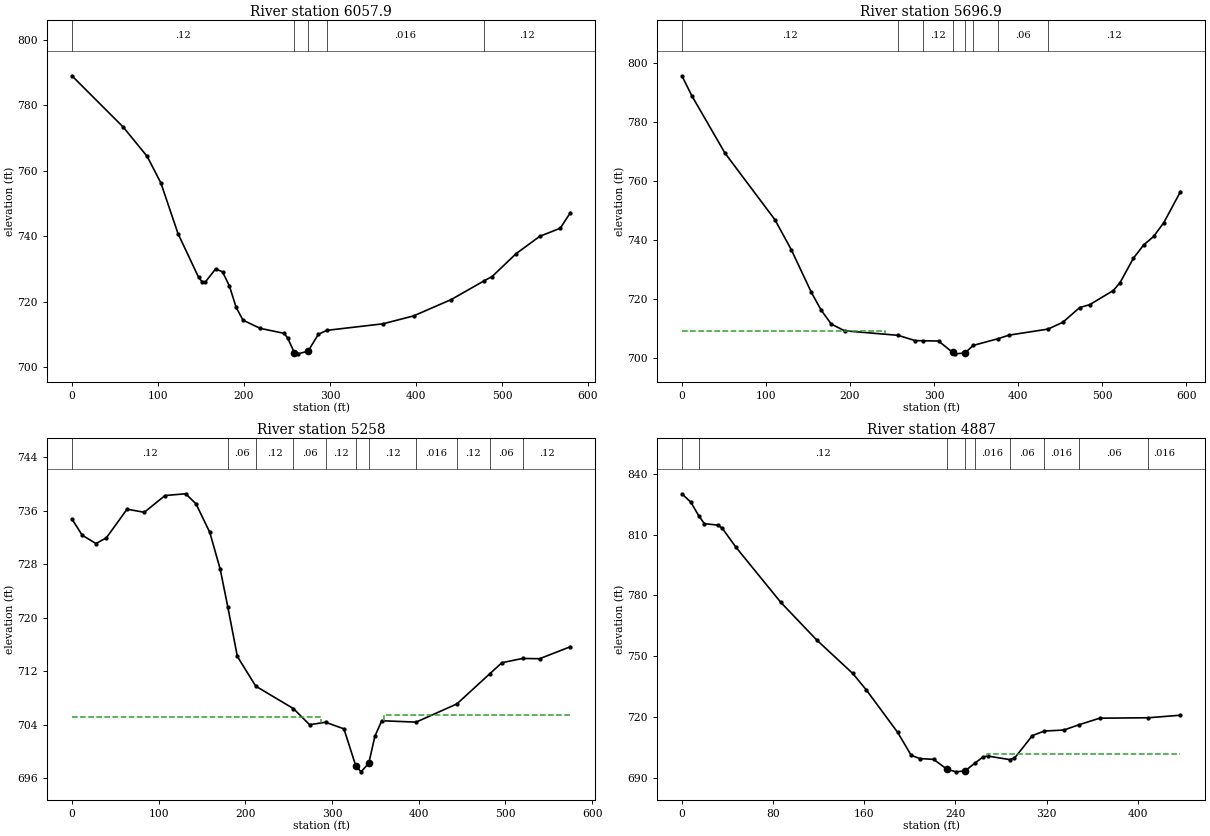
Type RM Length L Ch R = 1 ,6057.9  ,357,361,364.1
XS GIS Cut Line= 3
     1768353.515      431487.068      1768432.59      431762.406
     1768505.836      432046.232
#Sta/Elev= 30
       0  789.01    59.7  773.32    87.5  764.35   103.4  756.26   123.3  740.78
   147.2  727.42   151.2  726.09   155.2  725.99   167.1  729.98   175.1  729.06
     183   724.8     191  718.17   198.9  714.29   218.8   711.8   246.7  710.26
   250.7  708.89   258.6  704.37   262.6     704   274.5   704.8   286.5  709.96
   296.1 711.174   361.7  713.18   397.4  715.62     441   720.6  479.12726.3128
   488.5  727.63   516.2  734.59   543.9  739.93   567.7   742.4   579.6  747.21
#Mann= 5 ,-1 , 0
       0     .12       0   258.6    .045       0   274.5     .06       0
   296.1    .016       0  479.12     .12       0
Bank Sta=258.6,274.5
XS Rating Curve= 0 ,0
Exp/Cntr=0.3,0.1

Type RM Length L Ch R = 1 ,5696.9  ,415.8,438.9,462.2
XS GIS Cut Line= 3
     1768129.408      431524.904     1768067.695      431712.418
     1768115.051      432105.301
#Sta/Elev= 30
       0  795.51    11.8  788.74    51.3  769.29   110.6  746.79   130.3  736.52
     154  722.15   165.8  716.09   177.7  711.42   193.5  709.16  257.15707.6212
   277.4  705.83   286.9705.7838   305.3  705.69   321.9  701.87   325.3  701.35
   336.9  701.64   346.4704.1945  376.15706.4841   389.3  707.69  435.65709.7372
   453.2  712.06   473.2  717.02   485.2  718.02   513.2  722.79   521.2  725.46
   537.2  733.77   549.2  738.19   561.2  741.12   573.2  745.76   593.1  756.28
#Mann= 8 ,-1 , 0
       0     .12       0  257.15    .016       0   286.9     .12       0
   321.9    .045       0   336.9     .12       0   346.4    .016       0
  376.15     .06       0  435.65     .12       0
#XS Ineff= 2 , 0
          241.49  709.12
Permanent Ineff=
       F       F
Bank Sta=321.9,336.9
XS Rating Curve= 0 ,0
Exp/Cntr=0.3,0.1

Type RM Length L Ch R = 1 ,5258    ,386.3,371,356
XS GIS Cut Line= 3
     1767890.318      431461.972     1767793.716      431662.578
     1767518.905      431883.169
#Sta/Elev= 30
       0  734.76    11.9  732.33    27.8  731.08    39.8  731.95    63.6  736.23
    83.5  735.76   107.4  738.27   131.2  738.53   143.1  737.03     159  732.76
     171  727.27   179.9  721.53   190.8   714.2  212.03709.7537  255.48706.3987
   274.1  703.99  292.49704.3574   313.7  703.37   327.4  697.83   333.5  696.94
   342.4  698.23   349.4  702.26   357.3  704.58  397.03704.3784  443.99707.1005
  481.86711.6023   495.9  713.26  519.74713.8994   539.4  713.86     575  715.66
#Mann= 11 ,-1 , 0
       0     .12       0   179.9     .06       0  212.03     .12       0
  255.48     .06       0  292.49     .12       0   327.4    .045       0
   342.4     .12       0  397.03    .016       0  443.99     .12       0
  481.86     .06       0  519.74     .12       0
#XS Ineff= 2 , 0
          287.31   705.2  360.37          705.37
Permanent Ineff=
       F       F
Bank Sta=327.4,342.4
XS Rating Curve= 0 ,0
Exp/Cntr=0.3,0.1

Type RM Length L Ch R = 1 ,4887    ,342.1,342.6,342.6
XS GIS Cut Line= 3
     1767449.964      431314.168     1767396.064      431552.685
     1767350.878      431740.265
#Sta/Elev= 30
       0   830.1     7.9  825.91    14.9819.1415    19.7  815.36    31.6  814.64
    35.5  813.04    47.3  803.82    86.8  776.54   118.3  757.98   149.9   741.5
   161.7  733.47   189.3  712.46   201.2  701.12     209   699.5   220.9  699.14
   232.7  694.22   240.6  692.98   248.5  693.46  257.18697.2886   264.2  700.32
   268.2  700.79  287.56699.0232   291.8  699.68   307.5  710.83  317.94713.1038
   335.1  713.58  348.32716.1795   366.6  719.44  409.09  719.64   437.5   720.9
#Mann= 9 ,-1 , 0
       0      .1       0    14.9     .12       0   232.7    .045       0
   248.5     .12       0  257.18    .016       0  287.56     .06       0
  317.94    .016       0  348.32     .06       0  409.09    .016       0
#XS Ineff= 2 , 0
                           267.8          701.89
Permanent Ineff=
       F       F
Bank Sta=232.7,248.5
XS Rating Curve= 0 ,0
Exp/Cntr=0.3,0.1