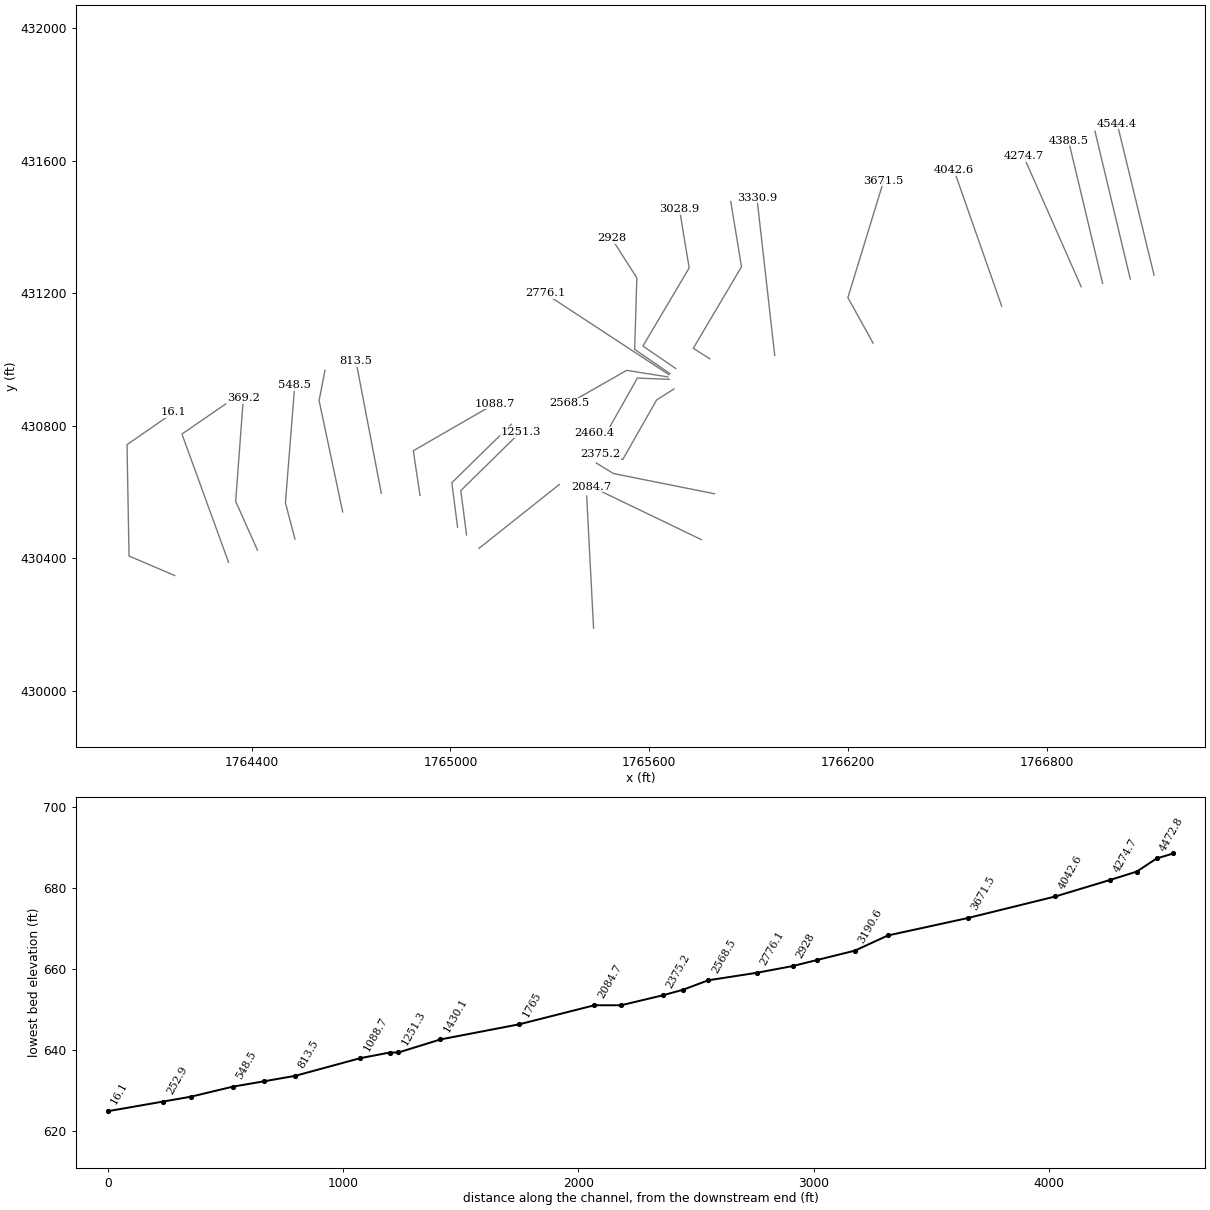
HEC-RAS study LICKCK.prj: LICKCK

--- LICKCK.g01 (geometry) --- (continued)

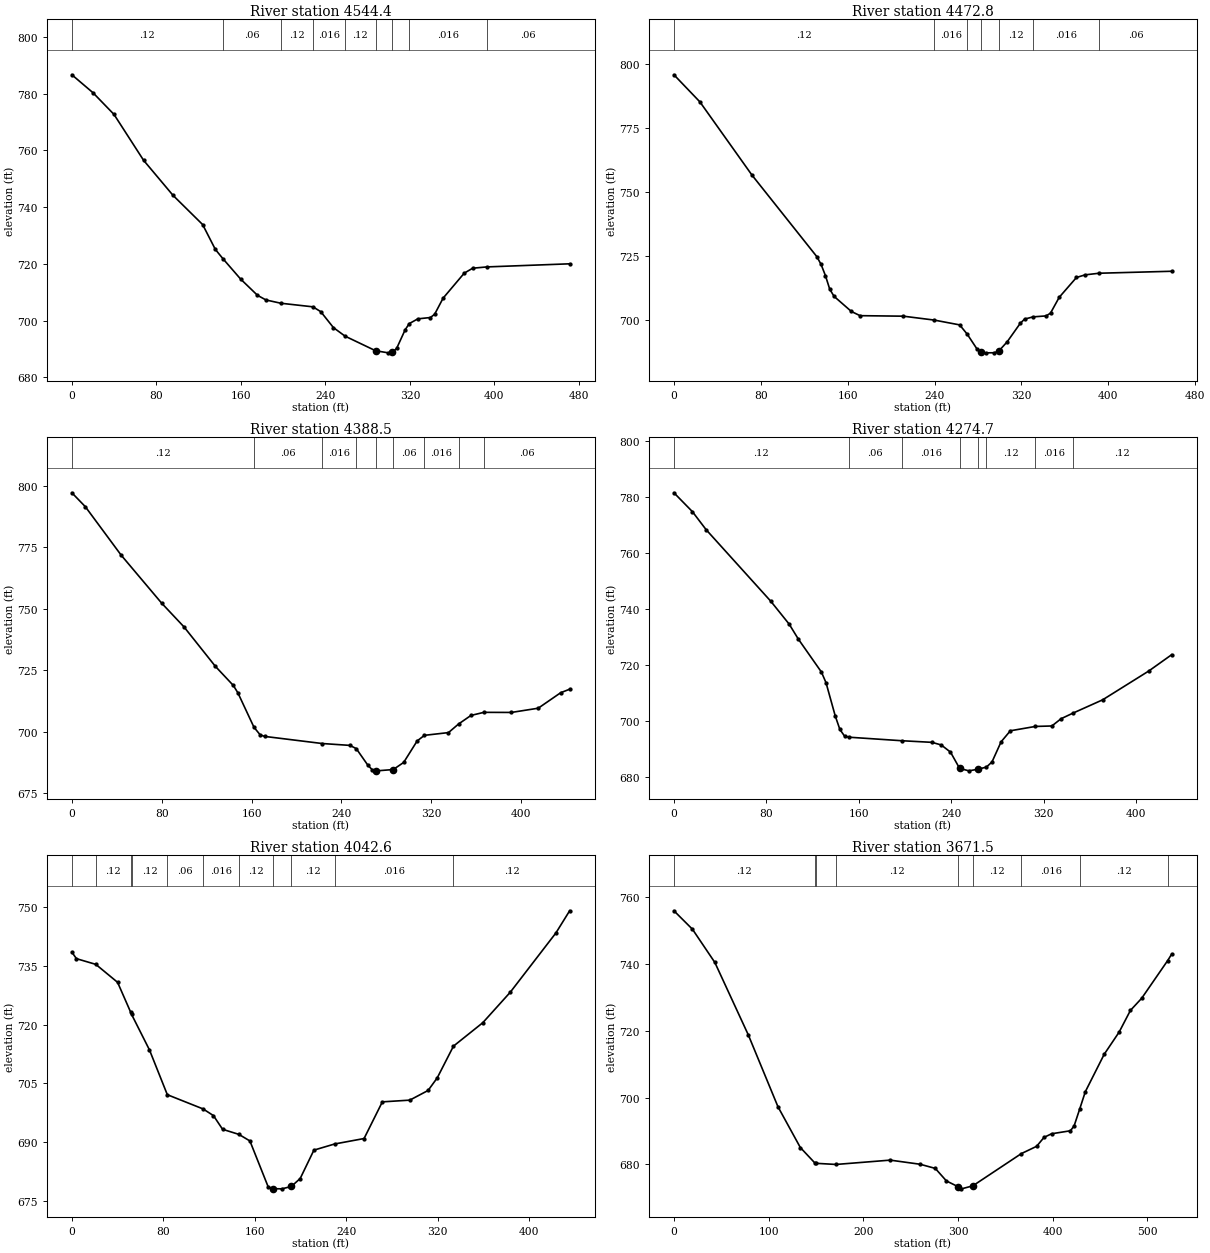
Type RM Length L Ch R = 1 ,4544.4  ,71.7,71.6,71.5
XS GIS Cut Line= 2
      1767123.25      431254.614     1767011.891      431712.507
#Sta/Elev= 30
       0  786.65      20  780.32    39.9  772.67    67.9   756.5    95.8  744.13
   123.8  733.85   135.8   725.1  142.96721.8396   159.7  714.66   175.7  708.92
   183.7  707.28  197.83706.1222  228.23704.8544   235.6  703.15   247.6  697.53
  258.62694.5189   287.5  689.38   299.5  688.64   303.5  688.78   307.5  690.26
   315.5  696.78  319.42698.9556   327.5  700.62   339.4  701.09   343.4  702.24
   351.4  707.91   371.4  716.72   379.4  718.47  392.94718.9276   471.2  720.02
#Mann= 9 ,-1 , 0
       0     .12       0  142.96     .06       0  197.83     .12       0
  228.23    .016       0  258.62     .12       0   287.5    .045       0
   303.5     .12       0  319.42    .016       0  392.94     .06       0
Bank Sta=287.5,303.5
XS Rating Curve= 0 ,0
Exp/Cntr=0.3,0.1

Type RM Length L Ch R = 1 ,4472.8  ,84.3,84.3,84.3
XS GIS Cut Line= 2
     1767051.451       431243.26     1766944.959      431689.133
#Sta/Elev= 30
       0  795.71    23.9  785.16    71.8  756.67   131.6  724.86   135.5  721.84
   139.5   717.5   143.5  712.16   147.5  709.38   163.4  703.51   171.4  701.87
   211.3  701.67  239.67700.1547   263.1  698.28  270.04694.6919     279  688.95
     283  687.57     287  687.39     295  687.42     299  688.02   306.9  691.69
   318.9  698.86   322.9  700.53  330.77701.4028   342.8  701.78   346.8  702.87
   354.8  709.02   370.7  716.75   378.7  717.77  391.51   718.4   458.4  719.17
#Mann= 7 ,-1 , 0
       0     .12       0  239.67    .016       0  270.04     .12       0
     283    .045       0     299     .12       0  330.77    .016       0
  391.51     .06       0
Bank Sta=283,299
XS Rating Curve= 0 ,0
Exp/Cntr=0.3,0.1

Type RM Length L Ch R = 1 ,4388.5  ,109.7,113.8,117.8
XS GIS Cut Line= 2
     1766967.954      431230.056     1766864.979      431661.204
#Sta/Elev= 30
       0  797.14      12  791.48    43.9  771.79    79.9  752.32    99.8  742.67
   127.8  726.61   143.8  718.84   147.8  715.89  162.15701.8798   167.7  698.76
   171.7  698.14  222.88695.2534   247.6  694.49  253.25693.1924   263.6  686.44
   267.6  684.53   271.2  684.19   271.6  684.15   286.2  684.68   295.5  687.57
   307.5   696.3  313.98698.5788   335.4  699.69  344.35 703.171   355.4  706.66
  366.92707.9188   391.4  707.88   415.3   709.6   435.3  715.89   443.3  717.32
#Mann= 9 ,-1 , 0
       0     .12       0  162.15     .06       0  222.88    .016       0
  253.25     .06       0   271.2    .045       0   286.2     .06       0
  313.98    .016       0  344.35     .12       0  366.92     .06       0
Bank Sta=271.2,286.2
XS Rating Curve= 0 ,0
Exp/Cntr=0.3,0.1

Type RM Length L Ch R = 1 ,4274.7  ,233.9,232.1,230.3
XS GIS Cut Line= 2
     1766903.266      431219.826     1766729.372      431613.849
#Sta/Elev= 30
       0  781.61      16  774.85    27.9  768.38    83.8  742.79    99.7   734.6
   107.7   729.2   127.6  717.45   131.6  713.62   139.6   701.7   143.6  696.88
   147.6  694.54  151.29694.1237   197.2692.8565   223.3  692.28   231.3  691.34
   239.3  688.78   247.2  682.95   255.2  682.08   263.2  682.67  270.35683.4188
   275.2  685.26   283.1  692.48   291.1  696.42  312.71697.9714     327  698.14
     335  700.74  344.99 702.688   370.9  707.49   410.8   717.8   430.7  723.66
#Mann= 8 ,-1 , 0
       0     .12       0  151.29     .06       0   197.2    .016       0
   247.2    .045       0   263.2     .06       0  270.35     .12       0
  312.71    .016       0  344.99     .12       0
Bank Sta=247.2,263.2
XS Rating Curve= 0 ,0
Exp/Cntr=0.3,0.1

Type RM Length L Ch R = 1 ,4042.6  ,385.3,371.1,356.7
XS GIS Cut Line= 2
     1766663.448      431161.265     1766519.289       431572.28
#Sta/Elev= 30
       0  738.56       4  736.89   20.93735.4347      40  730.84   51.42723.2191
   52.23722.6425    67.9  713.55   83.53702.0906  114.83698.4509   123.9  696.74
   131.9  693.24  146.13691.9442   155.8  690.26   171.8  678.51   175.8  678.05
   183.8  678.01     192  678.61   199.8  680.65   211.8  687.91   229.9689.4815
   255.7  690.88   271.7  700.26   295.7   700.7   311.7  703.17   319.7  706.38
  333.93714.5131   359.6  720.51   383.6  728.29   423.6  743.48   435.6  749.14
#Mann= 11 ,-1 , 0
       0     .08       0   20.93     .12       0   51.42     .08       0
   52.23     .12       0   83.53     .06       0  114.83    .016       0
  146.13     .12       0   175.8    .045       0     192     .12       0
   229.9    .016       0  333.93     .12       0
Bank Sta=175.8,192
XS Rating Curve= 0 ,0
Exp/Cntr=0.3,0.1

Type RM Length L Ch R = 1 ,3671.5  ,331,340.7,350
XS GIS Cut Line= 3
     1766275.392       431049.78     1766199.254      431187.101
     1766307.262      431539.626
#Sta/Elev= 30
       0  755.98    19.6  750.44    43.2  740.51    78.5  718.84   109.9  697.27
   133.5  685.07  148.48680.5594  150.06680.3461  171.15680.0031   228.4   681.3
   260.1  680.06     276  678.82   287.8  675.06   299.7   673.4   303.7   672.7
   315.6  673.59  366.89683.2497     383  685.43   390.9  688.12   398.8  689.19
   418.7  690.09   422.6  691.52  428.67696.7289   434.5  701.81   454.4     713
   470.2  719.66   482.1  726.14     494  729.78  521.35741.0273   525.7  743.01
#Mann= 9 ,-1 , 0
       0     .12       0  148.48     .08       0  150.06    .016       0
  171.15     .12       0   299.7    .045       0   315.6     .12       0
  366.89    .016       0  428.67     .12       0  521.35     .06       0
Bank Sta=299.7,315.6
XS Rating Curve= 0 ,0
Exp/Cntr=0.3,0.1

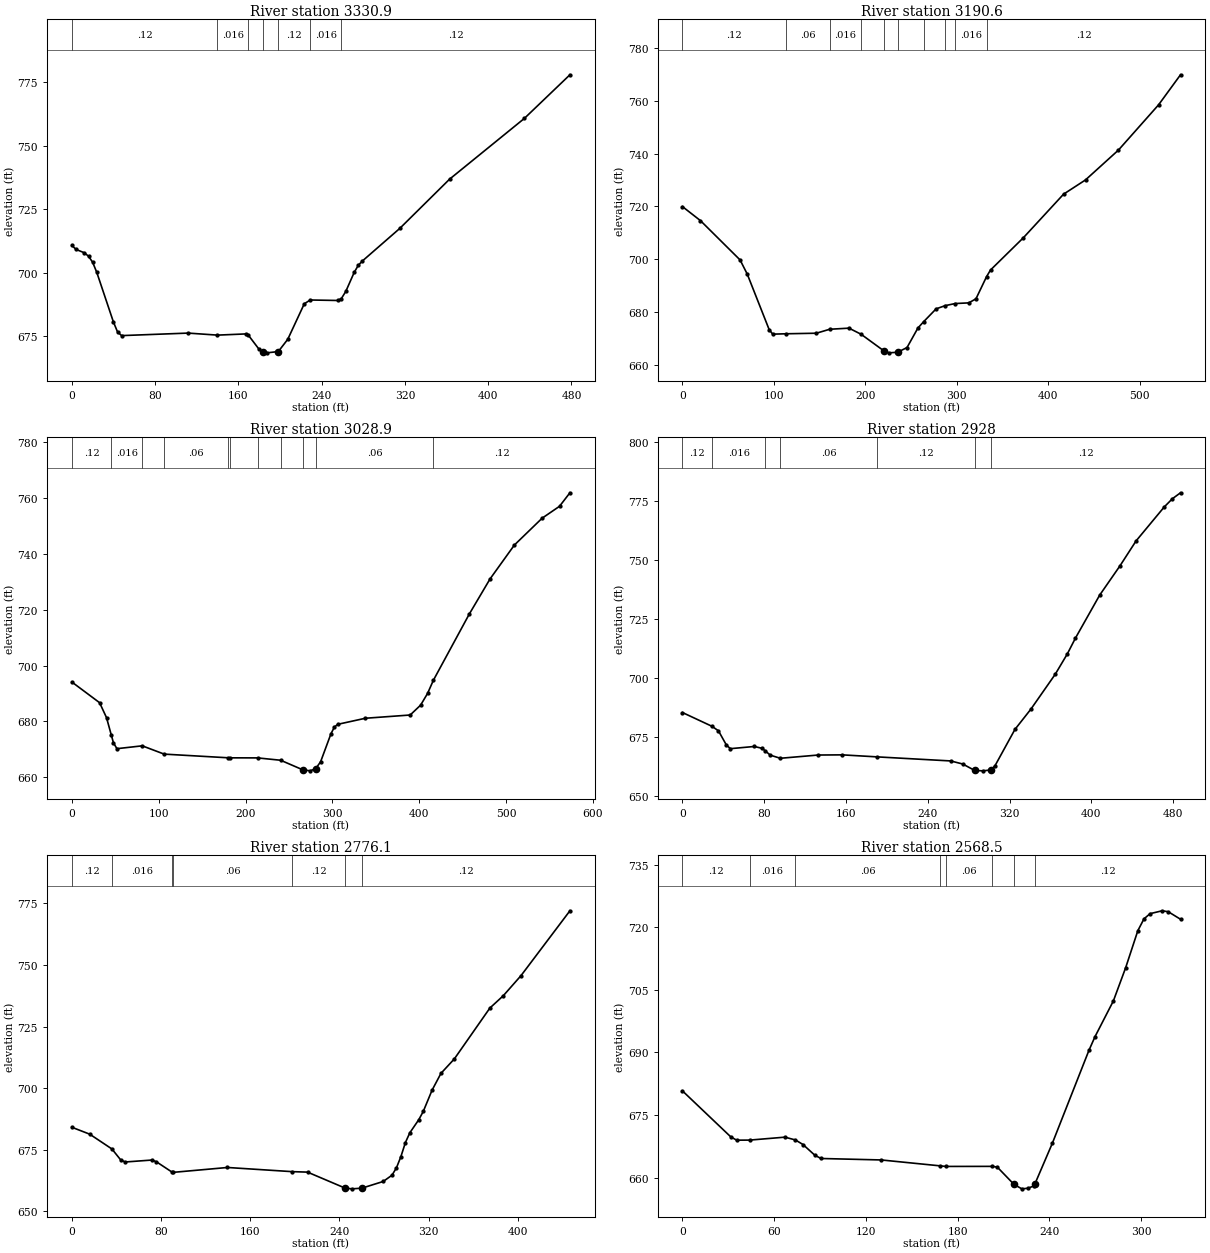
Type RM Length L Ch R = 1 ,3330.9  ,158.1,140.3,122.8
XS GIS Cut Line= 2
     1765978.508      431012.502     1765924.744      431488.016
#Sta/Elev= 30
       0   710.7       4  709.13      12  707.79      16  706.44    19.9   704.1
    23.9  700.11    39.9  680.55    43.9  676.58    47.8  675.17   111.7  676.16
  139.87675.3594   167.5  675.84  169.59675.3123   179.4  670.02   183.3  668.63
   187.4  668.38   198.3  668.88   207.4  673.71   223.3  687.72  229.04689.2009
   255.2  689.01  258.76689.6597   263.2  692.61   271.2  700.04   275.2  702.89
   279.2   704.6     315  717.39   362.9  736.81   434.7  760.73   478.5  777.93
#Mann= 7 ,-1 , 0
       0     .12       0  139.87    .016       0  169.59     .12       0
   183.3    .045       0   198.3     .12       0  229.04    .016       0
  258.76     .12       0
Bank Sta=183.3,198.3
XS Rating Curve= 0 ,0
Exp/Cntr=0.3,0.1

Type RM Length L Ch R = 1 ,3190.6  ,159.5,161.6,163.5
XS GIS Cut Line= 4
     1765782.497      431002.544     1765732.668      431034.171
     1765878.221      431280.156     1765845.755      431477.359
#Sta/Elev= 30
       0  719.94    19.7  714.63      63  699.77    70.9  694.38    94.8  673.43
    98.7   671.7  113.39671.8425   146.4  672.05  161.01673.5483   182.1  673.97
  195.33671.6677   220.3  665.37   225.8  664.63   235.3  664.86   245.6  666.64
   257.5  674.02  263.97 676.484   277.4  681.27  287.39682.4906  298.29683.2772
   313.1  683.53     321  685.07  332.61693.4736   336.9  695.96   372.8  708.15
   416.8  724.65   440.8  730.04   476.8  741.32   520.7  758.44   544.7  769.81
#Mann= 10 ,-1 , 0
       0     .12       0  113.39     .06       0  161.01    .016       0
  195.33     .06       0   220.3    .045       0   235.3     .06       0
  263.97    .016       0  287.39     .08       0  298.29    .016       0
  332.61     .12       0
Bank Sta=220.3,235.3
XS Rating Curve= 0 ,0
Exp/Cntr=0.3,0.1

Type RM Length L Ch R = 1 ,3028.9  ,88.7,101,113.4
XS GIS Cut Line= 4
     1765679.549      430973.286     1765580.737      431040.933
     1765720.235      431276.683     1765690.997       431454.28
#Sta/Elev= 30
       0  694.09    31.9   686.7    39.9  681.35   45.24675.3058    47.9  672.32
    51.9  670.24   81.04671.2608  106.31668.2945  179.57 666.988  182.47666.9662
  213.88666.9412  240.47 666.099   265.9  662.69   274.6  662.31   280.9  663.12
   286.5  665.55   298.4  675.55   302.4  677.99   306.3  678.96   338.1  681.13
   389.7  682.29   401.7  685.82   409.7     690  416.46694.7537   457.7  718.38
   481.7     731   509.7  743.11   541.7  752.73   561.7  756.98   573.7  761.82
#Mann= 11 ,-1 , 0
       0     .12       0   45.24    .016       0   81.04     .08       0
  106.31     .06       0  179.57     .12       0  182.47     .06       0
  213.88     .12       0  240.47     .06       0   265.9    .045       0
   280.9     .06       0  416.46     .12       0
Bank Sta=265.9,280.9
XS Rating Curve= 0 ,0
Exp/Cntr=0.3,0.1

Type RM Length L Ch R = 1 ,2928    ,128,151.9,175.5
XS GIS Cut Line= 4
     1765662.122       430957.95     1765555.808      431030.851
     1765562.318       431246.78     1765485.652      431366.707
#Sta/Elev= 30
       0  685.52   28.86   679.7    35.2  677.79      43  671.75    46.9  670.23
    70.3  671.16    78.1  670.36   81.08 669.275    85.9  667.49   95.76 666.164
   132.8  667.54   156.4  667.61   190.5 666.756   262.4  665.04   274.2  663.74
     286     661   293.9  660.85   301.7  661.21   305.7  662.94   325.3  678.38
     341  687.01   364.7   701.7   376.6  710.36   384.5  717.02   408.2   735.2
     428  747.55   443.8  758.13   471.5  772.57   479.4  776.01   487.3  778.51
#Mann= 7 ,-1 , 0
       0     .12       0   28.86    .016       0   81.08     .08       0
   95.76     .06       0   190.5     .12       0     286    .045       0
   301.7     .12       0
Bank Sta=286,301.7
XS Rating Curve= 0 ,0
Exp/Cntr=0.3,0.1

Type RM Length L Ch R = 1 ,2776.1  ,181.5,207.6,233.3
XS GIS Cut Line= 2
     1765659.308      430954.571     1765285.681      431199.604
#Sta/Elev= 30
       0  684.16      16  681.36   35.92675.3586    43.9  670.86    47.9  670.08
    71.8  670.87    75.8  670.17   89.78665.9968   91.08 665.883   139.6  667.85
  197.49666.1653   211.4  665.97   245.1  659.49   251.3  659.19   260.1  659.46
   279.3  662.18   287.2  664.73   291.2  667.74   295.2   672.3   299.2  677.96
   303.2  681.94   311.2  687.23   315.2  690.56   323.1  699.18   331.1  706.02
   343.1  711.88     375  732.52     387   737.5   402.9  745.65   446.8  771.96
#Mann= 7 ,-1 , 0
       0     .12       0   35.92    .016       0   89.78     .08       0
   91.08     .06       0  197.49     .12       0   245.1    .045       0
   260.1     .12       0
Bank Sta=245.1,260.1
XS Rating Curve= 0 ,0
Exp/Cntr=0.3,0.1

Type RM Length L Ch R = 1 ,2568.5  ,93.7,108.1,120.5
XS GIS Cut Line= 3
      1765656.09      430947.818     1765531.611      430967.609
     1765358.173      430868.651
#Sta/Elev= 30
       0  680.79    31.5  669.81    35.4  668.99   43.96669.0062      67  669.71
   73.86669.0394    78.8  667.95    86.6  665.37    90.6   664.6     130  664.25
  168.73662.8276   172.2662.6975  202.73662.7123   205.9  662.53  216.73658.4183
   221.9  657.33   225.9  657.47   229.9  658.04   230.5  658.52   241.9  668.26
   265.8  690.49   269.8   693.8   281.8  702.35   289.8  710.27   297.8  719.18
   301.8     722   305.8  723.25   313.7  723.94   317.7  723.71   325.7  721.91
#Mann= 8 ,-1 , 0
       0     .12       0   43.96    .016       0   73.86     .06       0
  168.73     .12       0   172.2     .06       0  202.73     .12       0
  216.73    .045       0   230.5     .12       0
Bank Sta=216.73,230.5
XS Rating Curve= 0 ,0
Exp/Cntr=0.3,0.1

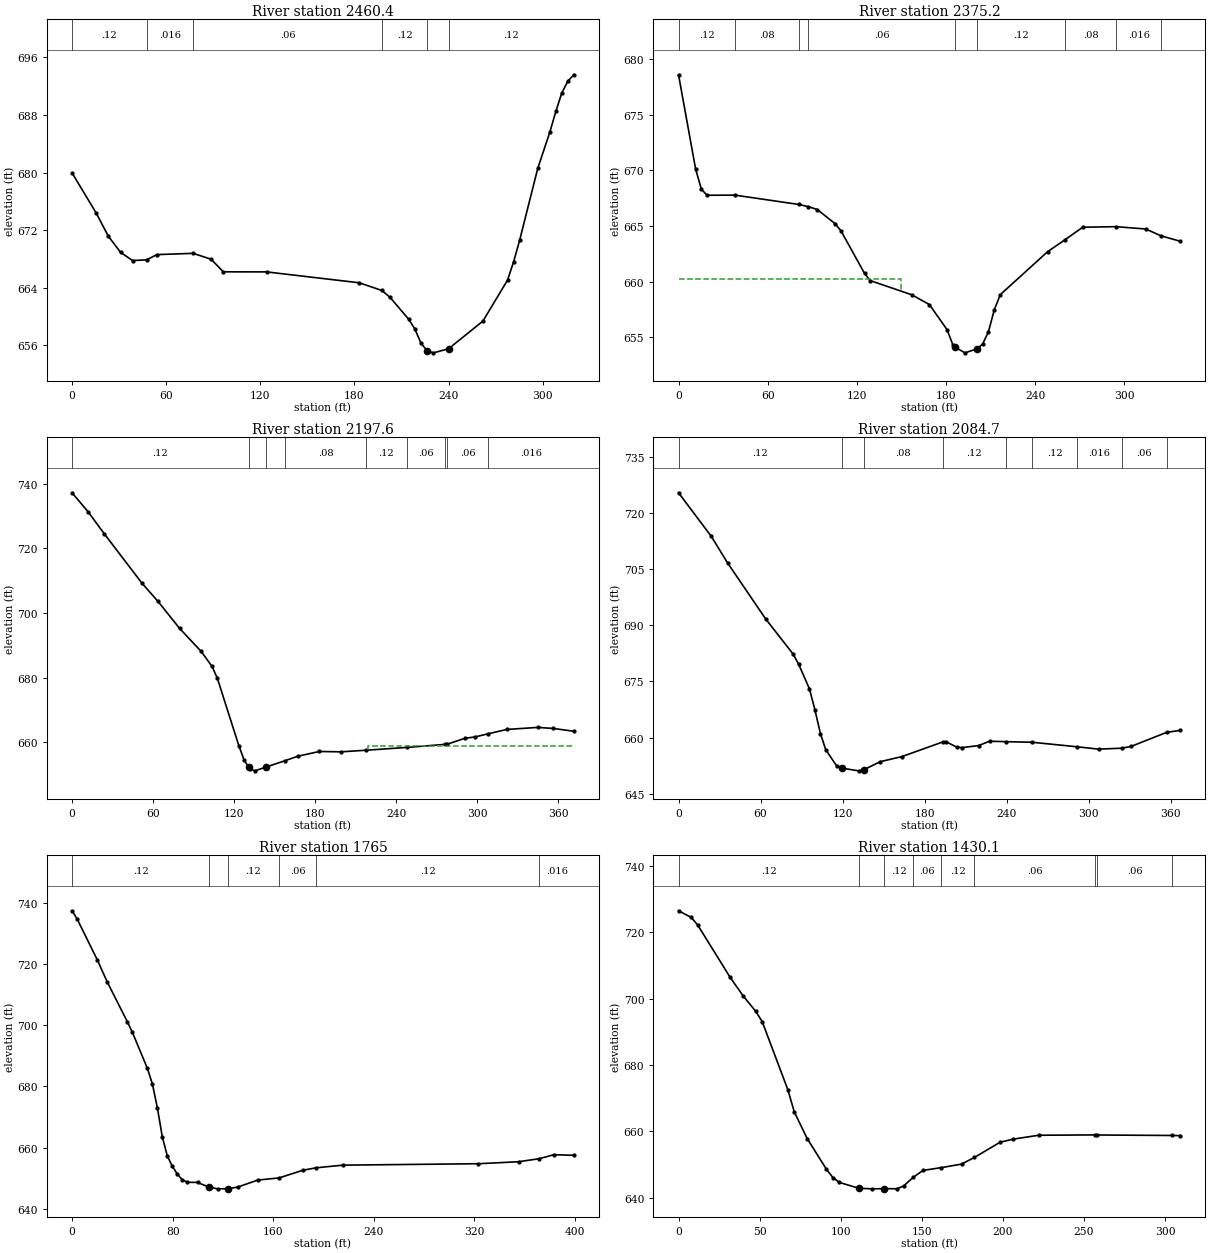
Type RM Length L Ch R = 1 ,2460.4  ,87.5,85.3,85.3
XS GIS Cut Line= 4
     1765660.257      430940.526     1765563.903      430944.172
      1765474.84      430786.359     1765433.173      430779.068
#Sta/Elev= 30
       0  679.94    15.4  674.37    23.1  671.17    30.9  668.93    38.6  667.78
   47.61667.8896      54  668.61   77.17668.7856    88.7  667.96    96.4  666.22
     124  666.21   183.1   664.7  197.52663.6311   202.8  662.66   214.6  659.64
   218.5   658.3   222.5   656.3   226.4  655.25   230.4  654.98     240 655.541
   261.9  659.38   277.6  665.06   281.5  667.62   285.3  670.57   296.9  680.59
   304.6  685.61   308.4  688.47   312.2  691.03   316.1  692.69   319.9  693.56
#Mann= 6 ,-1 , 0
       0     .12       0   47.61    .016       0   77.17     .06       0
  197.52     .12       0   226.4    .045       0     240     .12       0
Bank Sta=226.4,240
XS Rating Curve= 0 ,0
Exp/Cntr=0.3,0.1

Type RM Length L Ch R = 1 ,2375.2  ,206.1,177.5,148.5
XS GIS Cut Line= 4
     1765674.319      430911.359     1765622.236      430878.547
     1765520.038      430698.853     1765452.444      430715.005
#Sta/Elev= 30
       0  678.57    11.5  670.11    15.4   668.3    19.2  667.76   37.94667.7715
   80.89666.9357   87.35666.7379    93.4  666.48   105.3  665.22   109.3  664.58
   125.2  660.75   129.1   660.1     157  658.83   168.9  657.95   180.8  655.69
   184.8   654.3     186  654.14   192.8  653.62     201  653.98   204.7  654.41
   208.6   655.5   212.6   657.5   216.6  658.84   248.4  662.69  260.12663.7634
   272.1  664.89   294.5664.9415   314.6  664.73  324.87 664.115   337.8  663.63
#Mann= 9 ,-1 , 0
       0     .12       0   37.94     .08       0   80.89     .12       0
   87.35     .06       0     186    .045       0     201     .12       0
  260.12     .08       0   294.5    .016       0  324.87     .06       0
#XS Ineff= 2 , 0
           149.9  660.24
Permanent Ineff=
       F       F
Bank Sta=186,201
XS Rating Curve= 0 ,0
Exp/Cntr=0.3,0.1

Type RM Length L Ch R = 1 ,2197.6  ,118.4,113,107.7
XS GIS Cut Line= 3
     1765796.715      430595.214     1765492.028      430656.151
     1765439.944      430687.922
#Sta/Elev= 30
       0  737.22      12  731.27    23.9   724.5    51.8  709.23    63.7  703.58
    79.7  695.22    95.6  688.13   103.6  683.53   107.6  679.83   123.5     659
   127.5  654.44  130.82652.2737   131.5  651.83   135.4  651.16   143.4   652.3
  157.56654.2725   167.3  655.69   183.2  657.15   199.2  657.04   217.8657.5415
  247.92658.4015  276.18659.3425  278.04659.4188   290.8  661.21   298.8  661.68
  308.16662.6251   322.2  663.98     345   664.6   356.5  664.28   371.7   663.4
#Mann= 9 ,-1 , 0
       0     .12       0  130.82    .045       0   143.4     .12       0
  157.56     .08       0   217.8     .12       0  247.92     .06       0
  276.18     .12       0  278.04     .06       0  308.16    .016       0
#XS Ineff= 2 , 0
                           219.2          658.92
Permanent Ineff=
       F       F
Bank Sta=130.82,143.4
XS Rating Curve= 0 ,0
Exp/Cntr=0.3,0.1

Type RM Length L Ch R = 1 ,2084.7  ,344.1,319.7,295.4
XS GIS Cut Line= 2
     1765757.132      430456.672     1765426.403      430616.047
#Sta/Elev= 30
       0  725.34    23.9  713.75    35.9  706.61    63.8  691.66    83.8  682.32
    87.8  679.67    95.8     673    99.8  667.39   103.8  661.12   107.7  656.78
   115.7  652.47   119.7  651.87   131.7  651.16   135.7  651.49   147.6  653.61
   163.6  654.98  193.14658.8461   195.5  658.97   203.5  657.48   207.5  657.36
   219.5   657.9   227.5  659.06  239.79658.9437  258.71658.7838  291.49657.5815
   307.3  656.95  324.28657.1962   331.2  657.69  357.07661.4209   367.1  661.96
#Mann= 9 ,-1 , 0
       0     .12       0   119.7    .045       0   135.7     .08       0
  193.14     .12       0  239.79     .06       0  258.71     .12       0
  291.49    .016       0  324.28     .06       0  357.07     .12       0
Bank Sta=119.7,135.7
XS Rating Curve= 0 ,0
Exp/Cntr=0.3,0.1

Type RM Length L Ch R = 1 ,1765    ,356.7,334.9,313.1
XS GIS Cut Line= 2
     1765431.784      430189.484     1765410.951      430588.095
#Sta/Elev= 30
       0  737.56       4   734.9      20  721.54    27.9   714.3    43.9  701.27
    47.9  697.82    59.9  685.94    63.9  680.82    67.9  672.93    71.8  663.45
    75.8  657.17    79.8  653.84    83.8  651.24    87.8  649.37    91.8  648.61
    99.8  648.56   108.8  647.03   115.8  646.46   123.8  646.49   131.7  647.03
   147.7  649.33  164.76650.0453   183.6  652.55  194.34653.3654   215.5  654.22
   323.3  654.69   355.2  655.34  371.79656.3434   383.2  657.64   399.2  657.46
#Mann= 6 ,-1 , 0
       0     .12       0   108.8    .045       0   123.8     .12       0
  164.76     .06       0  194.34     .12       0  371.79    .016       0
Bank Sta=108.8,123.8
XS Rating Curve= 0 ,0
Exp/Cntr=0.3,0.1

Type RM Length L Ch R = 1 ,1430.1  ,176.4,178.8,181.1
XS GIS Cut Line= 2
     1765085.951      430430.457     1765328.141      430622.971
#Sta/Elev= 30
       0  726.46     7.9  724.44    11.9   722.1    31.7   706.5    39.7  700.92
    47.6  696.17    51.6  693.08    67.4  672.57    71.4  665.85    79.3  657.88
    91.2  648.61    95.2  646.11    99.2  644.64   111.1  642.91     119  642.72
   126.9  642.77   134.9  642.75   138.8  643.59  144.64646.1588   150.7  648.27
  161.96649.1021   174.5  650.17  182.37652.1594   198.3  656.76   206.3  657.68
   222.1  658.86  256.89658.9605  257.83658.9394  304.35658.7905   309.4  658.74
#Mann= 9 ,-1 , 0
       0     .12       0   111.1    .045       0   126.9     .12       0
  144.64     .06       0  161.96     .12       0  182.37     .06       0
  256.89     .08       0  257.83     .06       0  304.35    .016       0
Bank Sta=111.1,126.9
XS Rating Curve= 0 ,0
Exp/Cntr=0.3,0.1

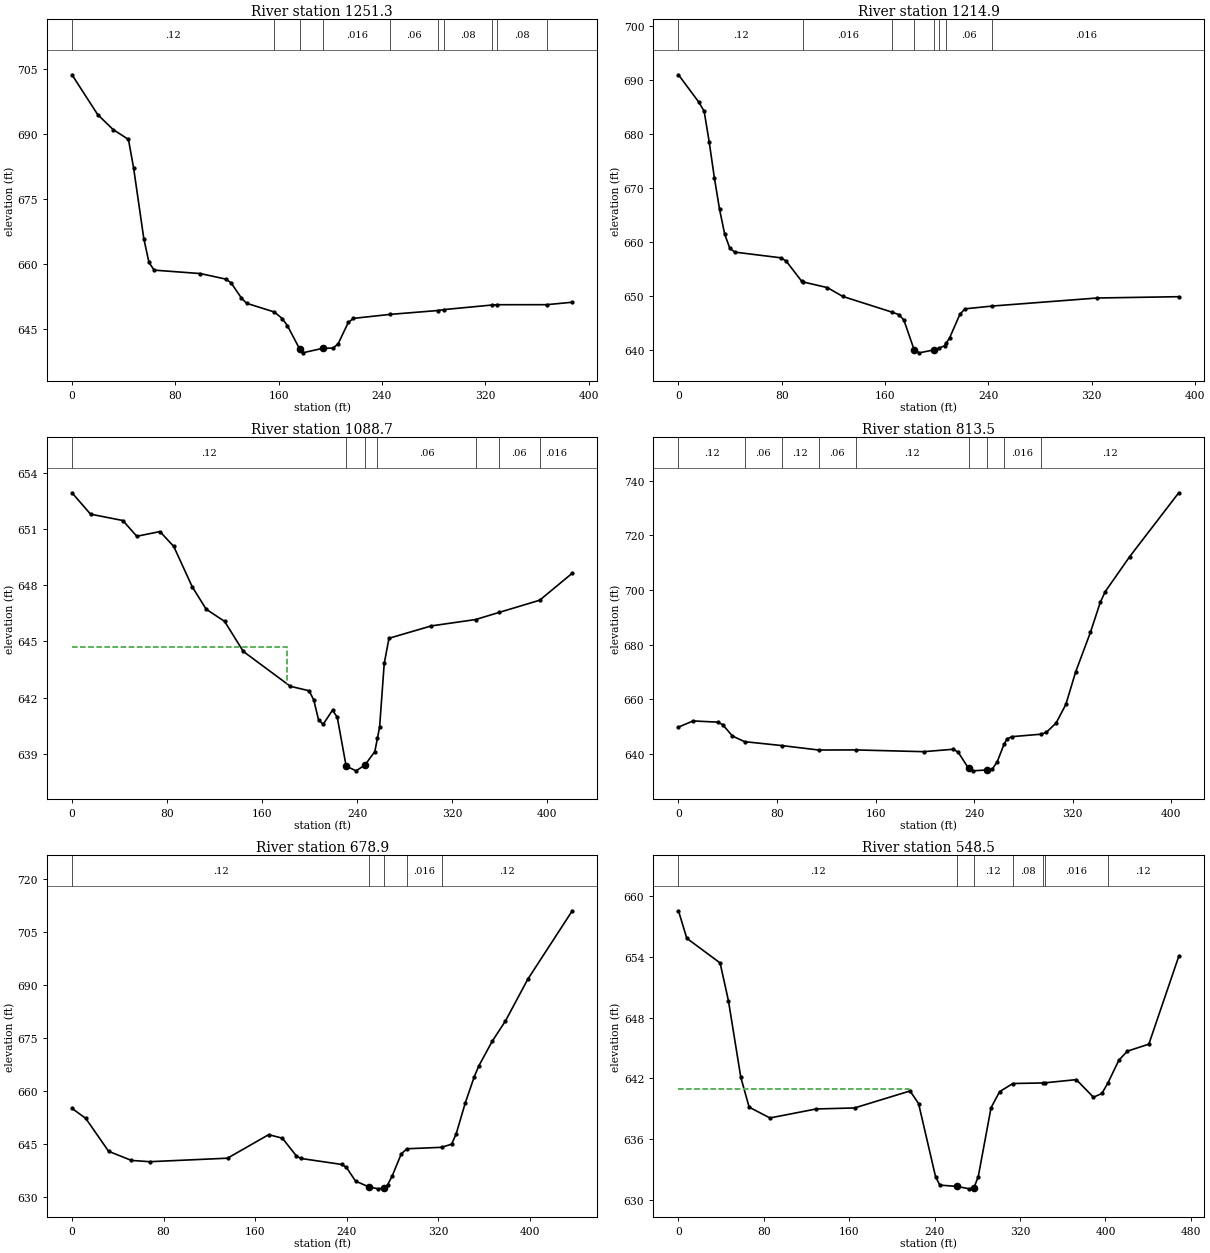
Type RM Length L Ch R = 1 ,1251.3  ,36.3,36.4,36.3
XS GIS Cut Line= 3
     1765048.451      430470.734      1765031.09      430604.762
     1765211.008      430781.365
#Sta/Elev= 30
       0  703.72    19.9  694.52    31.8  691.08    43.7  688.79    47.7   682.2
    55.6  665.87    59.6  660.37    63.6   658.6    99.4  657.81   119.2  656.52
   123.2  655.65   131.2  652.15   135.2  650.94  156.67 648.936   162.7  647.43
   166.7  645.81  176.37640.3201   178.5   639.5   194.2  640.55   202.1   640.6
     206  641.56   213.9  646.52   217.9  647.46  246.52648.3872  283.16649.2706
  287.91649.4866  325.33650.5485   329.3650.6151  367.49650.6211   387.3  651.19
#Mann= 10 ,-1 , 0
       0     .12       0  156.67    .016       0  176.37    .045       0
   194.2    .016       0  246.52     .06       0  283.16    .016       0
  287.91     .08       0  325.33    .016       0   329.3     .08       0
  367.49    .016       0
Bank Sta=176.37,194.2
XS Rating Curve= 0 ,0
Exp/Cntr=0.3,0.1

Type RM Length L Ch R = 1 ,1214.9  ,132,126.2,120.6
XS GIS Cut Line= 3
     1765021.368      430494.345     1765004.007      430628.373
     1765183.924      430804.976
#Sta/Elev= 30
       0  690.95    15.9  685.84    19.9  684.19    23.8  678.52    27.8  671.89
    31.8  666.07    35.8  661.44    39.8  658.81    43.7  658.13    79.5  657.07
    83.5  656.44    95.4  652.74   96.76652.5938   115.3  651.56   127.2  649.93
  165.13 647.037   170.6  646.57   174.5  645.56   182.4   640.1   186.4  639.49
   198.2  640.05   201.7640.3461     206   640.8  207.29641.2816     210   642.3
   217.9  646.63   221.8  647.63  243.09648.1534   324.2  649.64   387.3  649.88
#Mann= 8 ,-1 , 0
       0     .12       0   96.76    .016       0  165.13     .12       0
   182.4    .045       0   198.2     .12       0   201.7    .016       0
  207.29     .06       0  243.09    .016       0
Bank Sta=182.4,198.2
XS Rating Curve= 0 ,0
Exp/Cntr=0.3,0.1

Type RM Length L Ch R = 1 ,1088.7  ,246.6,275.3,303.7
XS GIS Cut Line= 3
     1764907.964      430590.207     1764887.825      430724.929
     1765134.353       430867.29
#Sta/Elev= 30
       0  652.92    15.6  651.78    42.8  651.44    54.5   650.6      74  650.85
    85.6  650.06   101.2   647.9   112.9  646.71   128.4  646.06   144.1  644.46
   183.7   642.6   199.5  642.36   203.4  641.87   207.4  640.82   211.3  640.57
   219.2  641.33   223.2  640.94  230.65638.3423     239  638.09   246.5   638.4
   254.8  639.12  257.01639.8383   258.8  640.42   262.7  643.82   266.7  645.16
   302.3  645.82  339.51646.1583  359.33646.5389  393.44647.1884   420.9  648.63
#Mann= 7 ,-1 , 0
       0     .12       0  230.65    .045       0   246.5     .12       0
  257.01     .06       0  339.51     .12       0  359.33     .06       0
  393.44    .016       0
#XS Ineff= 2 , 0
           180.6  644.68
Permanent Ineff=
       F       F
Bank Sta=230.65,246.5
XS Rating Curve= 0 ,0
Exp/Cntr=0.3,0.1

Type RM Length L Ch R = 1 ,813.5   ,134.4,134.5,134.7
XS GIS Cut Line= 2
      1764791.17      430596.699     1764714.683      430995.408
#Sta/Elev= 30
       0  649.76    11.9  652.02    31.8  651.57    35.8   650.7    43.8   646.5
   53.64644.4275   83.71643.0029  113.79641.3642  143.86641.3998     199  640.76
   222.9  641.64   226.9  640.64   235.4  634.67   238.8  633.74   250.4  634.07
   254.7  634.39   258.7  637.06  264.16643.3953   266.7  645.44   270.6  646.26
  294.23647.1559   298.5  647.81   306.5  651.26   314.4  658.07   322.4  670.04
   334.3  684.42   342.3   695.4   346.3  699.35   366.2  712.19     406  735.58
#Mann= 9 ,-1 , 0
       0     .12       0   53.64     .06       0   83.71     .12       0
  113.79     .06       0  143.86     .12       0   235.4    .045       0
   250.4     .12       0  264.16    .016       0  294.23     .12       0
Bank Sta=235.4,250.4
XS Rating Curve= 0 ,0
Exp/Cntr=0.3,0.1

Type RM Length L Ch R = 1 ,678.9   ,141.8,130.4,120.7
XS GIS Cut Line= 3
     1764674.546       430540.47     1764603.429      430876.481
     1764621.287        430968.1
#Sta/Elev= 30
       0  655.11      12  652.28      32  642.97    51.9   640.4    67.9  640.04
   135.8  641.03   171.7  647.68   183.7  646.68   195.7  641.76   199.7  640.96
   235.6  639.26   239.6  638.43   247.6  634.55   259.6  632.87   267.6  632.37
  272.61632.6828   275.6  633.52   279.6  636.02   287.5  642.25  292.46 643.692
  322.65644.1021   331.5     645   335.5  647.96   343.4  656.66   351.2  664.01
   355.1  667.05   366.8  674.01   378.5  679.83   397.9  691.56   436.8  710.94
#Mann= 5 ,-1 , 0
       0     .12       0   259.6    .045       0  272.61     .12       0
  292.46    .016       0  322.65     .12       0
Bank Sta=259.6,272.61
XS Rating Curve= 0 ,0
Exp/Cntr=0.3,0.1

Type RM Length L Ch R = 1 ,548.5   ,174.8,179.3,182
XS GIS Cut Line= 3
     1764530.497      430458.571     1764501.867      430567.887
     1764529.918       430922.34
#Sta/Elev= 30
       0  658.57     7.8  655.85      39  653.41    46.8  649.68    58.4   642.1
    66.2  639.15    85.7  638.08     129  638.97   164.9  639.07   216.9  640.75
   224.9  639.51   240.8  632.28   244.8  631.44   260.8  631.31   272.6  631.07
   276.8  631.19   280.8  632.27   292.8  639.09   300.8  640.68  313.26641.4869
  341.04641.5417  342.89 641.551   372.7  641.87   388.7  640.13   396.6   640.5
  402.14641.5134   412.6  643.81   420.6  644.69   440.6  645.38   468.6  654.05
#Mann= 7 ,-1 , 0
       0     .12       0   260.8    .045       0   276.8     .12       0
  313.26     .08       0  341.04     .12       0  342.89    .016       0
  402.14     .12       0
#XS Ineff= 2 , 0
           216.2  640.95
Permanent Ineff=
       F       F
Bank Sta=260.8,276.8
XS Rating Curve= 0 ,0
Exp/Cntr=0.3,0.1

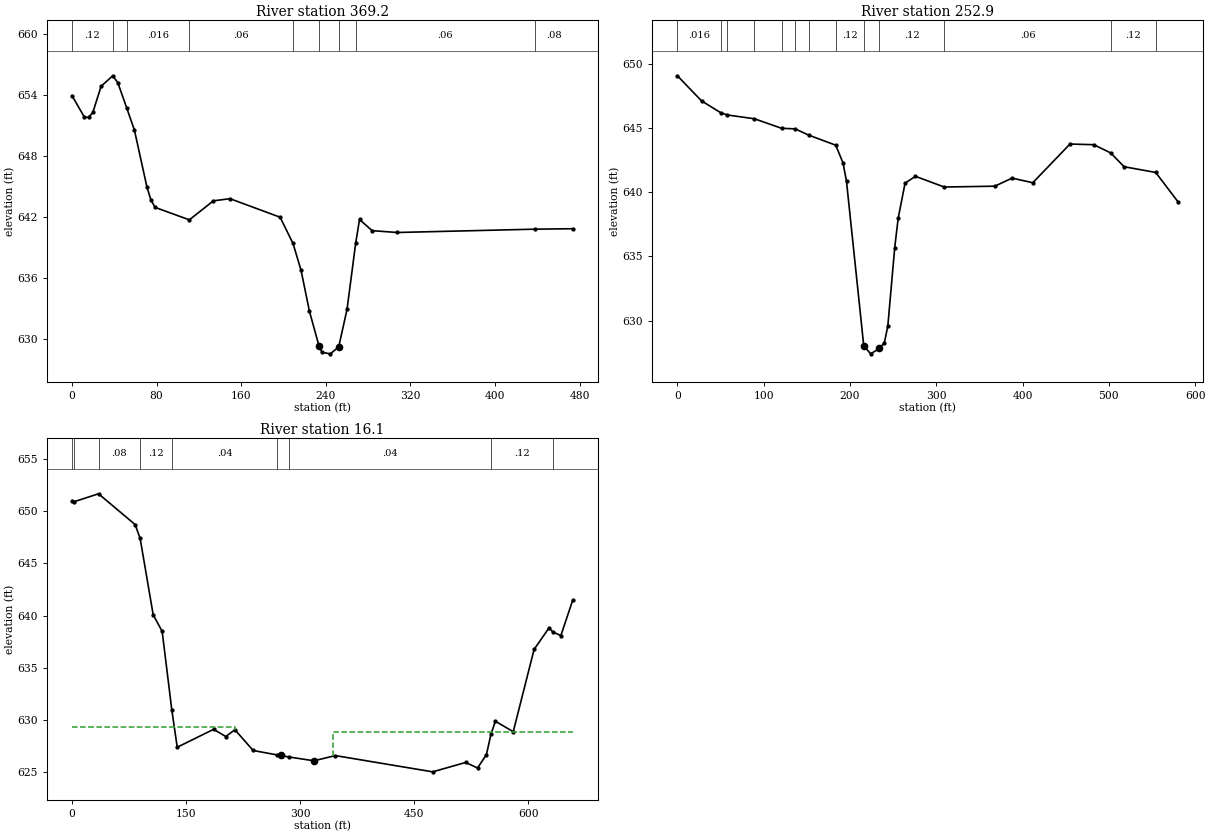
Type RM Length L Ch R = 1 ,369.2   ,105.6,116.3,127
XS GIS Cut Line= 3
     1764417.399      430424.979     1764351.693      430572.227
     1764374.854      430883.703
#Sta/Elev= 30
       0  653.94    11.8  651.81    15.7  651.82    19.7   652.3    27.5  654.86
   38.49655.8934    43.3  655.22   51.67652.7504      59  650.56    70.8  644.99
    74.7  643.67    78.7  642.96  110.97641.7411   133.7  643.61   149.4  643.82
   196.8     642  208.99639.4204   216.6  636.79   224.5  632.77   233.5  629.38
   236.4  628.73   244.3  628.58   252.2  629.26   260.1  632.96  268.22 639.421
   271.9  641.78   283.8  640.68   307.5   640.5   437.5 640.825   473.6  640.87
#Mann= 9 ,-1 , 0
       0     .12       0   38.49     .08       0   51.67    .016       0
  110.97     .06       0  208.99     .12       0   233.5    .045       0
   252.2     .12       0  268.22     .06       0   437.5     .08       0
Bank Sta=233.5,252.2
XS Rating Curve= 0 ,0
Exp/Cntr=0.3,0.1

Type RM Length L Ch R = 1 ,252.9   ,244.2,236.8,229.3
XS GIS Cut Line= 3
     1764330.222      430388.269     1764189.597      430775.422
     1764328.486      430870.908
#Sta/Elev= 30
       0  649.11      28  647.15   50.13646.2308   57.83646.0508   89.26645.7532
  120.68645.0115  136.64 644.964   152.1 644.478  183.53643.6906     192   642.3
     196  640.86     216  628.02     224   627.4   234.1  627.82   239.9  628.26
   243.9  629.58   251.9   635.7   255.9  637.99   263.9  640.73   275.9  641.26
  309.22640.4244   367.9  640.49   387.9  641.12   411.9  640.76     455  643.78
   482.5  643.73  502.22643.0868   517.7  642.01  554.36641.5617   580.4  639.25
#Mann= 13 ,-1 , 0
       0    .016       0   50.13     .08       0   57.83     .06       0
   89.26     .08       0  120.68     .06       0  136.64     .08       0
   152.1     .06       0  183.53     .12       0     216    .045       0
   234.1     .12       0  309.22     .06       0  502.22     .12       0
  554.36     .06       0
Bank Sta=216,234.1
XS Rating Curve= 0 ,0
Exp/Cntr=0.3,0.1

Type RM Length L Ch R = 1 ,16.1    ,16,16.1,16.1
XS GIS Cut Line= 4
     1764167.896      430348.339     1764029.875      430407.366
     1764023.798      430743.304     1764165.291      430841.394
#Sta/Elev= 30
       0  651.01    2.68650.9229   34.81651.6868      83  648.73   89.56 647.395
   106.7  640.07   118.5  638.48  131.18 630.936   138.3  627.36   186.1  629.08
   202.1  628.39   214.1  629.04   238.1  627.05   269.8  626.62   274.1  626.57
   284.8  626.43   318.1  626.06   346.1  626.56   474.1     625   517.4   625.9
   533.1  625.37   544.8  626.66  550.63628.5972   556.5  629.86     580  628.85
   607.4  636.75     627  638.81  632.29638.4089   642.6  638.08   658.3   641.5
#Mann= 9 ,-1 , 0
       0     .08       0    2.68     .06       0   34.81     .08       0
   89.56     .12       0  131.18     .04       0   269.8    .045       0
   284.8     .04       0  550.63     .12       0  632.29     .06       0
#XS Ineff= 2 , 0
          213.83  629.26  343.14           628.8
Permanent Ineff=
       F       F
Bank Sta=274.1,318.1
XS Rating Curve= 0 ,0
Exp/Cntr=0.3,0.1
LCMann Table=0

Chan Stop Cuts=-1
Use User Specified Reach Order=0
Composite Channel Slope=5